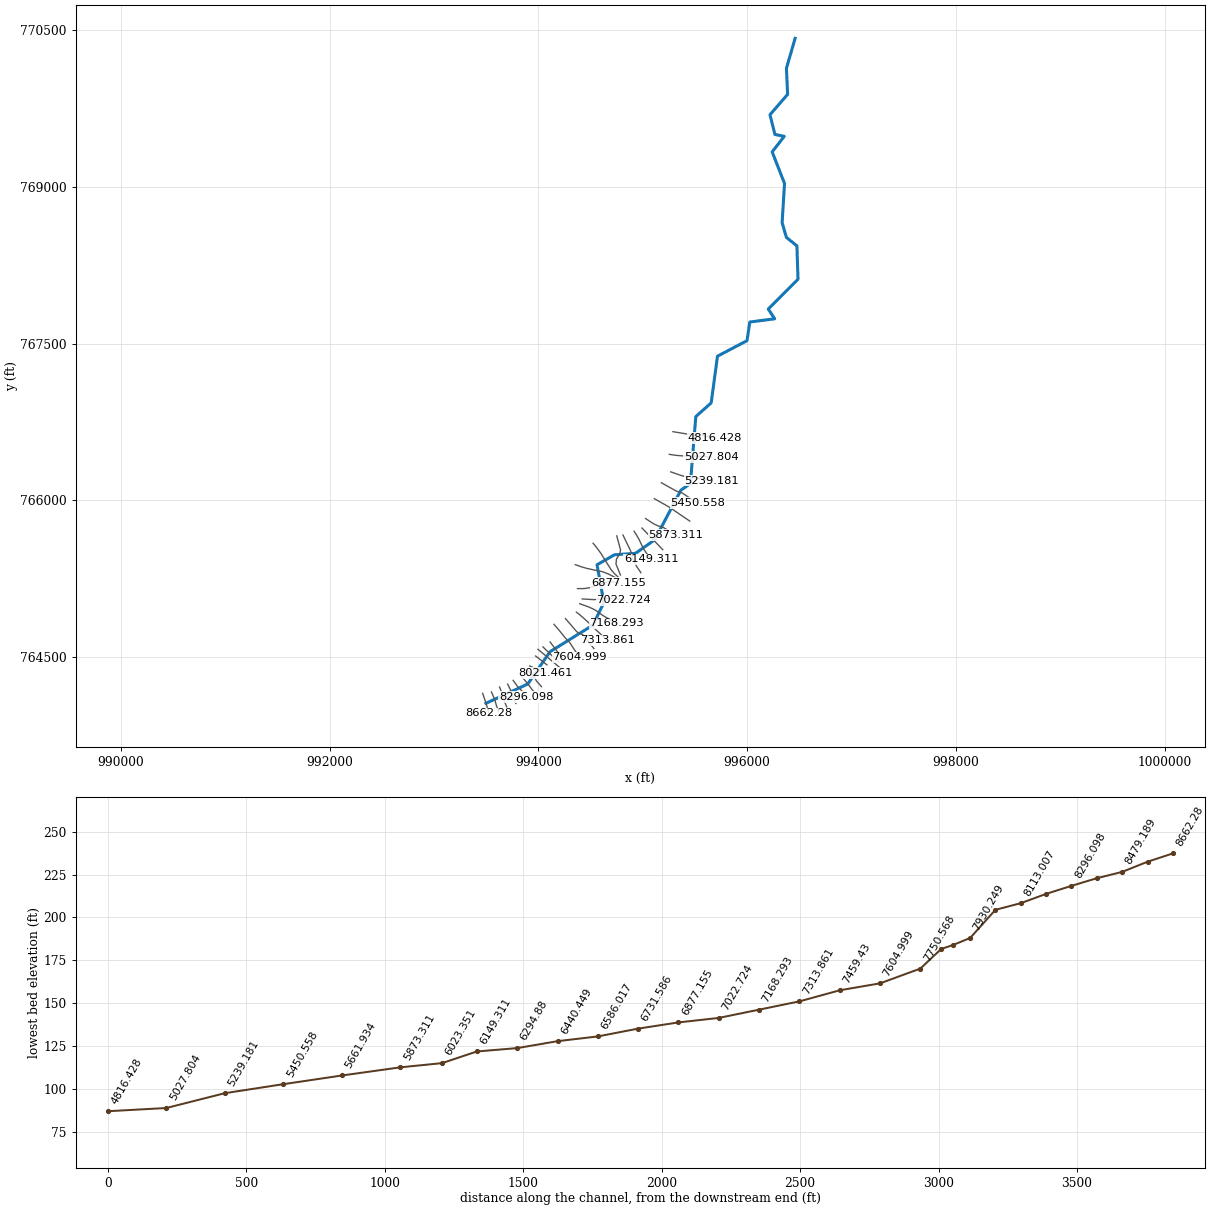
--- 156_ras.prj (project) ---

Proj Title=156
Current Plan=p01
Default Exp/Contr=0.3,0.1
English Units
Geom File=g01
Flow File=f01
Plan File=p01
Y Axis Title=Elevation
X Axis Title(PF)=Main Channel Distance
X Axis Title(XS)=Station
BEGIN DESCRIPTION:
RFD model 156 exported to HEC-RAS
END DESCRIPTION:

--- 156_ras.p01 (plan) ---

Plan Title=Plan 01
Program Version=4.10
Short Identifier=Plan 01
Geom File=g01
Flow File=f01
Subcritical Flow
Calc Critical at every XS
Secant Critical Depth

--- 156_ras.f01 (steady flow) ---

Flow Title=Flow 01
Program Version=5.01
Number of Profiles= 6
Profile Names=10yr,25yr,50yr,100yr,100plus,500yr
River Rch & RM=156,59, 8662.28
   92.14  175.58  265.54  364.87  532.71 1208.76
River Rch & RM=156,59,6586.017
   94.55  180.22  272.61  374.63  546.97 1236.78
River Rch & RM=156,59,6440.449
   95.76  182.54  276.14   379.5  554.07  1250.7
River Rch & RM=156,59, 6294.88
   97.76  186.38  281.99  387.58  565.86 1273.76
River Rch & RM=156,59,6149.311
  103.91  198.21  300.01  412.44  602.16 1344.24
River Rch & RM=156,59,6023.351
  106.07  202.36  306.32  421.16   614.9  1368.9
River Rch & RM=156,59,5873.311
  108.99  207.98  314.89     433  632.19 1402.25
River Rch & RM=156,59,5661.934
  112.27  214.31  324.54  446.34  651.65 1439.67
River Rch & RM=156,59,5450.558
  114.57  218.75  331.31   455.7  665.32 1465.86
River Rch & RM=156,59,5239.181
  115.91  221.33  335.25  461.14  673.27 1481.05
River Rch & RM=156,59,5027.804
  118.58  226.48   343.1  471.99   689.1 1511.25
River Rch & RM=156,59,4816.428
   119.9  229.03     347  477.38  696.97 1526.26
River Rch & RM=156,59,4605.051
  140.05  267.87  406.27  559.31  816.59 1751.09
River Rch & RM=156,59, 4465.92
  273.95  526.25  800.85 1104.82 1613.03  3153.9
River Rch & RM=156,59,4333.709
  274.87  528.05  803.63 1108.68 1618.67 3163.55
River Rch & RM=156,59,4114.051
  280.73  539.47  821.19 1133.09 1654.31 3224.41
River Rch & RM=156,59,3892.361
  283.19  544.26  828.56 1143.33 1669.27  3249.9
River Rch & RM=156,59,3670.671
  289.98  557.47  848.84  1171.5  1710.4 3319.59
River Rch & RM=156,59, 3448.98
  297.47  572.06  871.27 1202.67  1755.9 3396.53
River Rch & RM=156,59,3190.863
  297.93  572.95  872.64 1204.57 1758.68 3401.22
River Rch & RM=156,59,2982.976
  303.09  583.02  888.11 1226.08 1790.08 3454.18
River Rch & RM=156,59,2775.089
   303.7   584.2  889.93 1228.61 1793.77 3460.39
River Rch & RM=156,59,2567.202
  307.91  592.41  902.57  1246.2 1819.46 3503.74
River Rch & RM=156,59,2359.316
  308.49  593.57  904.35 1248.69 1823.09 3509.91
River Rch & RM=156,59,2151.429
  310.69  597.89  911.03 1258.01  1836.7 3533.03
River Rch & RM=156,59,2016.877
  315.37  607.07  925.23 1277.85 1865.66 3582.16
River Rch & RM=156,59,1887.429
   316.1  608.51  927.44 1280.94 1870.17 3589.81
River Rch & RM=156,59,1642.829
  322.39  620.85  946.51 1307.54 1909.01 3655.35
River Rch & RM=156,59, 1398.23
  325.29  626.55  955.31 1319.84 1926.97 3685.68
River Rch & RM=156,59,1153.631
  326.59  629.11  959.28 1325.38 1935.05 3699.29
River Rch & RM=156,59,779.7729
  328.16   632.2  964.07 1332.08 1944.84 3715.91
River Rch & RM=156,59,560.1416
   329.7  635.26  968.82 1338.75 1954.58 3732.49
River Rch & RM=156,59,340.5102
  331.38  638.59  973.99 1346.02 1965.18 3750.55
River Rch & RM=156,59,253.8634
   331.8  639.42  975.29 1347.83 1967.83 3755.06
River Rch & RM=156,59,119.1512
  332.08  639.98  976.15 1349.04  1969.6 3758.07
River Rch & RM=156,59, 51.7951
  333.21   642.2   979.6 1353.89 1976.67 3770.08
Boundary for River Rch & Prof#=156,59,1
Up Type= 0
Dn Type= 2
Boundary for River Rch & Prof#=156,59,2
Up Type= 0
Dn Type= 2
Boundary for River Rch & Prof#=156,59,2
Up Type= 0
Dn Type= 2
Boundary for River Rch & Prof#=156,59,2
Up Type= 0
Dn Type= 2
Boundary for River Rch & Prof#=156,59,2
Up Type= 0
Dn Type= 2
Boundary for River Rch & Prof#=156,59,2
Up Type= 0
Dn Type= 2

--- 156_ras.g01 (geometry) ---

Geom Title=156
Program Version=4.10

River Reach=156,59
Reach XY= 30
993498.069719225764055.575972095993898.527435303 764239.77410011
994112.056963235764549.391370639994523.064871609764803.872925714
994628.089005411765019.980278015994562.448921829 765381.50566183
994729.073749542765477.441168696994932.053085089765491.579032868
995114.835471869765620.839505285995366.287484586766096.477649882
995457.173754305766159.088191167995508.675973803766800.341316059
995656.113700122766931.621483371    995716.61462 767378.73285906
995999.539141834767527.529858932 996025.78861478767705.842776343
996264.520191878767736.820943788996202.864706099767830.279380322
996488.013122499 768115.69660455996477.362844735768434.857833639
996376.354433268 768516.44585824996335.850780308768657.830518737
996358.863206655769032.085241914996240.331275105769334.839252263
996356.440845966769483.855506405996266.937180579769501.402835295
996219.537654489769690.739360541996388.385872304769885.353532016
996377.030911624770135.470526025996460.358325601770421.900325477

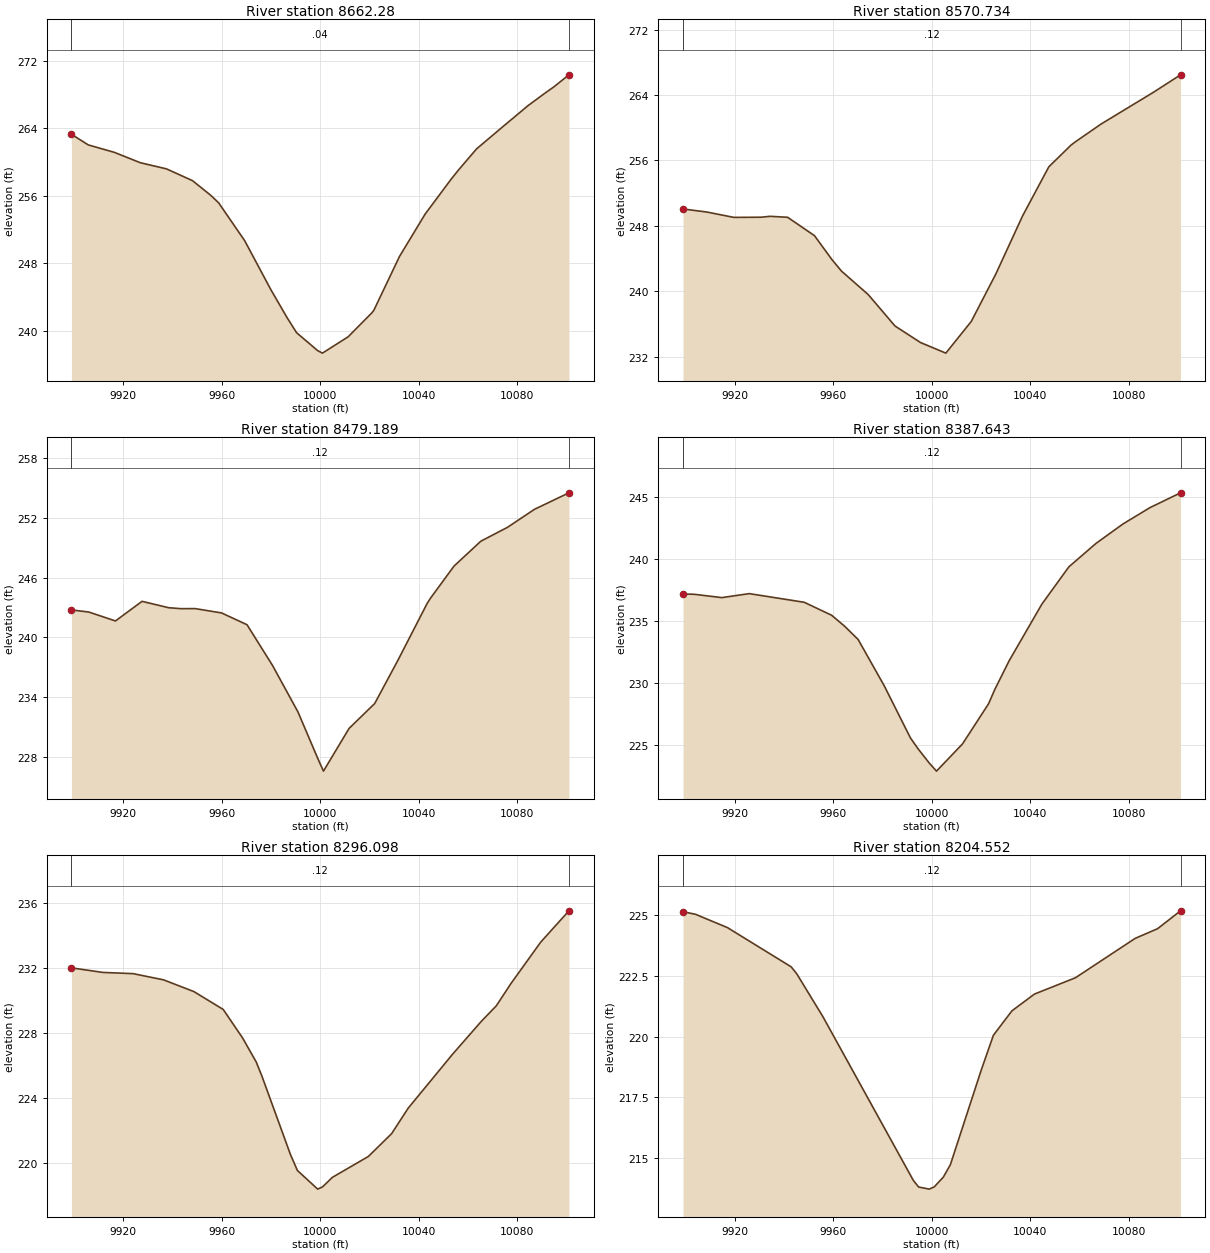
Type RM Length L Ch R = 1 , 8662.28,91.545500,91.545500,91.545500
XS GIS Cut Line= 5
993466.452675171764151.454013268993493.041094248764074.857697515
993498.728270571764056.827495217993499.321242347764054.917420749
993527.744887991763959.045536555
#Sta/Elev= 30
9899.014263.27099905.846262.01169916.431261.13169925.079260.11979927.017259.8957
9937.602259.17029948.187257.76949955.573256.03339958.773255.14699969.358250.6523
9979.943244.86849980.094244.78789986.606241.50939990.431239.7391    9999 237.612
10000.91237.3176   10001237.332910011.34239.248710020.98242.093610021.77 242.383
 10032.2248.777210042.63253.812710053.07257.904910056.16259.0356 10063.5261.5401
10073.93264.114710084.36266.660610091.34268.164510094.79268.8731   10101 270.322
#Mann= 3 , 0 , 0
9899.014    0.04       09899.014    0.04       0   10101    0.04       0
#XS Ineff= 2 , 0
       0                               0
Bank Sta=9899.014,10101
Exp/Cntr=0.3,0.1

Type RM Length L Ch R = 1 ,8570.734,91.545600,91.545600,91.545600
XS GIS Cut Line= 6
993550.818301507764163.899428705993584.640065262764086.608403142
993588.732963055 764071.56378978993588.877511575764069.569020188
993595.436605606764043.658381459993619.717046004763974.570555119
#Sta/Elev= 22
9899.041250.07739908.756249.70029919.671249.04749930.587249.06699934.417249.1773
9941.502249.06069952.418246.81119959.362243.94039963.333242.49259974.249239.6038
9985.075235.77679995.439233.756210005.71 232.46210016.03236.332410025.95242.1005
10036.91249.262410047.51255.227910056.57257.8943 10058.1258.2416 10068.7260.4517
 10089.9264.320310100.96266.4671
#Mann= 3 , 0 , 0
9899.041    0.12       09899.041    0.12       010100.96    0.12       0
#XS Ineff= 2 , 0
       0                               0
Bank Sta=9899.041,10100.96
Exp/Cntr=0.3,0.1

Type RM Length L Ch R = 1 ,8479.189,91.545500,91.545500,91.545500
XS GIS Cut Line= 6
993628.412663114 764211.58460914993650.600571009764156.430832941
993660.945104007764117.270081657993661.430175257764115.329796656
993669.750776094764086.060166336 993697.08213045764022.117703768
#Sta/Elev= 23
9899.047242.76319906.144242.54639916.923241.65099927.702243.62499938.481242.9855
 9943.49242.88789949.259242.89489959.976242.45939970.319241.27189980.662 237.178
9991.005232.4928    9999227.838510001.34226.543310011.74  230.8410022.14233.3476
10031.43237.633710043.46243.431310044.78243.941510054.33247.171810065.21249.6747
10076.08251.078310086.96252.880210100.97 254.542
#Mann= 3 , 0 , 0
9899.047    0.12       09899.047    0.12       010100.97    0.12       0
#XS Ineff= 2 , 0
       0                               0
Bank Sta=9899.047,10100.97
Exp/Cntr=0.3,0.1

Type RM Length L Ch R = 1 ,8387.643,91.545500,91.545500,91.545500
XS GIS Cut Line= 6
993706.312187069764239.142682513993734.146859725764182.470573617
993746.522157754764147.799347622993747.071600011764145.876299727
993756.889418041764117.080182004993785.523203546764053.701420459
#Sta/Elev= 23
9899.048237.16799903.663237.14019914.804236.87289925.945237.19439948.227236.4967
9959.368235.44739964.724 234.5479970.119233.49219980.736229.74129991.354225.5351
9994.472224.6538    9999223.504710001.93222.854910012.49225.054510023.06 228.296
10025.57229.442210031.42231.774310044.68236.341210055.65239.358510066.63241.2473
 10077.6242.821210088.57244.143110100.97 245.338
#Mann= 3 , 0 , 0
9899.048    0.12       09899.048    0.12       010100.97    0.12       0
#XS Ineff= 2 , 0
       0                               0
Bank Sta=9899.048,10100.97
Exp/Cntr=0.3,0.1

Type RM Length L Ch R = 1 ,8296.098,91.545500,91.545500,91.545500
XS GIS Cut Line= 6
993758.959215466764275.343294591993799.627889216764218.946956115
993820.707304395764197.016637542993831.384491465764186.611082883
993842.545605308764173.163491583993881.511551362 764115.50736022
#Sta/Elev= 23
9899.051232.01999911.803231.73889924.132231.66289936.461231.2818 9948.79230.5575
9960.669229.45919968.582227.69279974.056226.22789976.334225.37169987.927 220.544
9990.764219.5536    9999218.4057   10001218.546710004.96  219.1310019.57220.4161
   10029221.818510035.77223.395210053.63226.685810065.38 228.72510071.49229.6845
10077.45231.058110089.52233.604810100.97235.5286
#Mann= 3 , 0 , 0
9899.051    0.12       09899.051    0.12       010100.97    0.12       0
#XS Ineff= 2 , 0
       0                               0
Bank Sta=9899.051,10100.97
Exp/Cntr=0.3,0.1

Type RM Length L Ch R = 1 ,8204.552,91.545600,91.545600,91.545600
XS GIS Cut Line= 5
993835.704299302764318.939805694993899.139008409764241.647246864
993900.462186625764240.147513751993902.791311562 764237.28695308
993960.594494671764160.252544761
#Sta/Elev= 20
9899.009225.15389904.106225.04579917.043224.49839942.916  222.889945.188222.5937
9955.853220.81639992.476214.08029994.663 213.799    9999213.7116   10001213.8041
10004.69214.205510007.55214.717110020.05218.610110025.03220.058410032.55221.0651
10041.69 221.75610058.35222.429810082.56224.052210091.68224.4527   10101225.1899
#Mann= 3 , 0 , 0
9899.009    0.12       09899.009    0.12       0   10101    0.12       0
#XS Ineff= 2 , 0
       0                               0
Bank Sta=9899.009,10101
Exp/Cntr=0.3,0.1

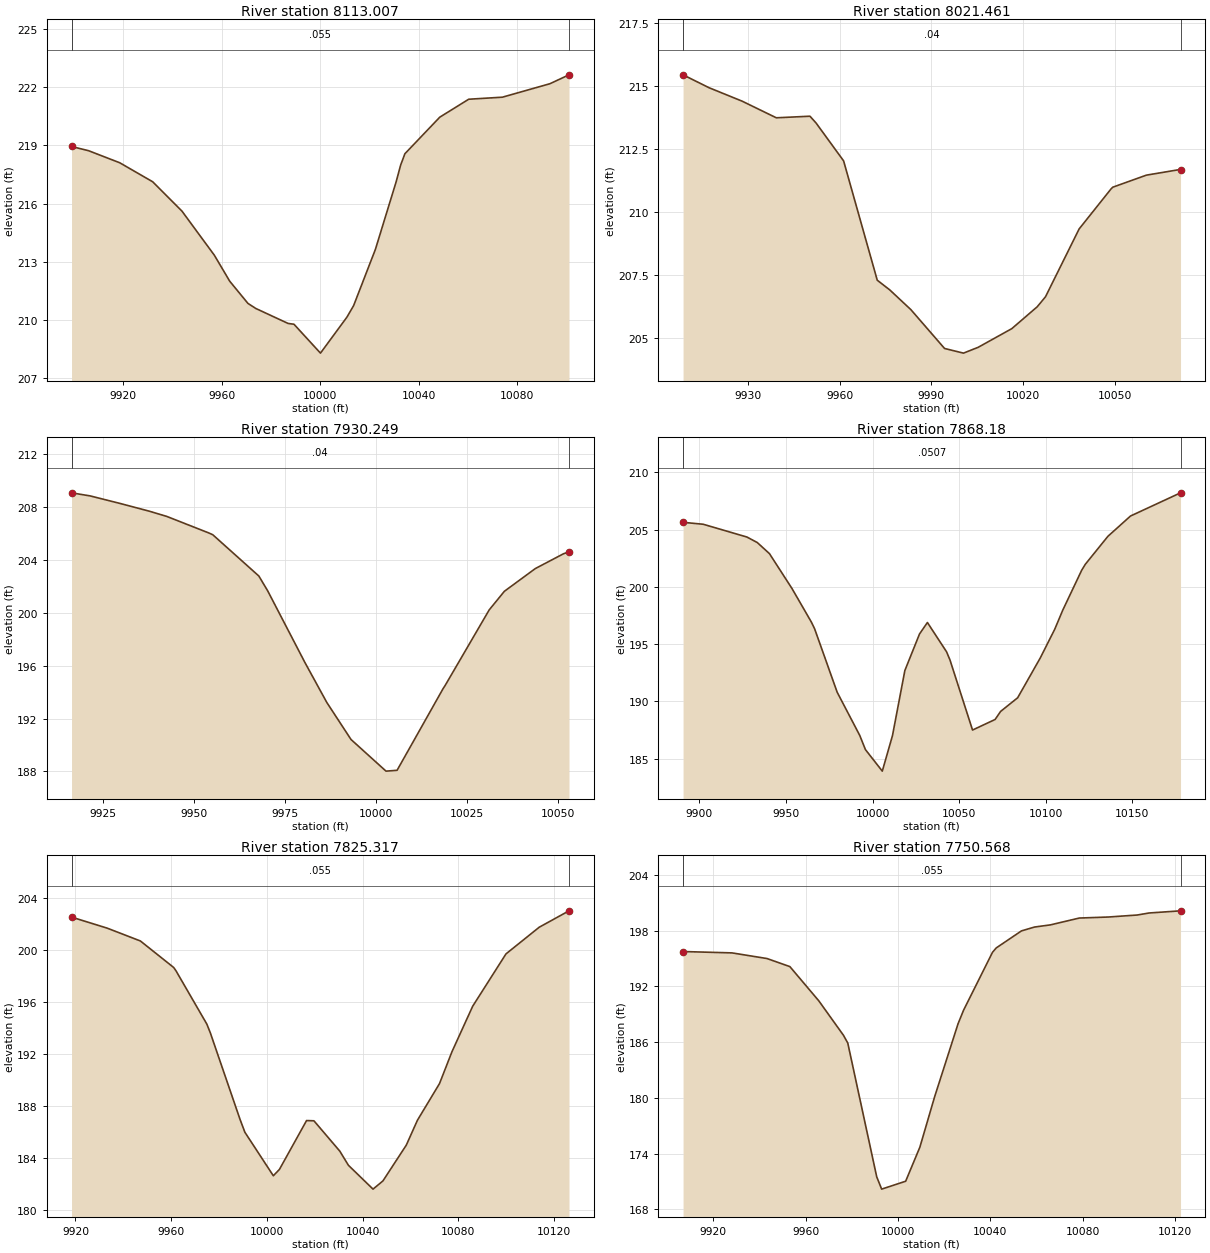
Type RM Length L Ch R = 1 ,8113.007,91.545500,91.545500,91.545500
XS GIS Cut Line= 6
993899.526211124764365.125902664993957.370970565764317.787369219
993965.183176672764306.906653446993973.979687348764284.298744671
993983.848728268764267.768768792994030.261012165764215.218287201
#Sta/Elev= 23
9899.076218.93629905.991218.71899918.623218.09969932.015217.11989943.888215.6106
9957.029213.34249963.271212.00469970.656210.86349973.887210.59979986.968209.8316
9989.339209.791210000.09208.3049 10010.8210.150710013.54210.747510022.38213.6419
 10030.8217.118510032.63217.982110034.36218.563910048.51220.444310060.25221.3672
10073.92221.472510093.23222.166510100.95222.6229
#Mann= 3 , 0 , 0
9899.076   0.055       09899.076   0.055       010100.95   0.055       0
#XS Ineff= 2 , 0
       0                               0
Bank Sta=9899.076,10100.95
Exp/Cntr=0.3,0.1

Type RM Length L Ch R = 1 ,8021.461,91.212300,91.212300,91.212300
XS GIS Cut Line= 2
993917.287290812764413.039974004994065.136349291764345.557001263
#Sta/Elev= 23
9908.865215.44449917.343214.93439928.228214.39789928.335214.39099939.327213.7423
 9950.32213.80469952.311213.53669961.312212.03579972.305207.30829976.394206.9234
9983.297206.1409 9994.29204.603410000.48204.418810005.28204.649410016.27205.3893
10024.56206.254210027.27206.650710038.26209.338610048.64210.917110049.25210.9923
10060.24211.470210071.24211.693710071.39211.6933
#Mann= 3 , 0 , 0
9908.865    0.04       09908.865    0.04       010071.39    0.04       0
#XS Ineff= 2 , 0
       0                10067.92       0
Bank Sta=9908.865,10071.39
Exp/Cntr=0.3,0.1

Type RM Length L Ch R = 1 ,7930.249,62.068800,62.068800,62.068800
XS GIS Cut Line= 2
993974.341076821764508.129617453994082.313833237764424.082642272
#Sta/Elev= 22
 9916.31209.07579917.145209.03679921.405208.84429929.817208.26119937.685207.6877
 9942.49207.29259953.965206.05119955.162205.90379967.835202.78069970.245201.6696
9980.507196.23599986.525193.2157 9993.18190.4151 10002.8188.021610005.85188.0837
10018.52194.268810019.08194.5071 10031.2200.222710035.36201.625810043.87203.3451
10051.64204.467610053.14204.6086
#Mann= 3 , 0 , 0
 9916.31    0.04       0 9916.31    0.04       010053.14    0.04       0
#XS Ineff= 2 , 0
       0                               0
Bank Sta=9916.31,10053.14
Exp/Cntr=0.3,0.1

Type RM Length L Ch R = 1 , 7868.18,42.862700,42.862700,42.862700
XS GIS Cut Line= 2
 993996.70185411 764572.46171546994217.187965214764388.433937684
#Sta/Elev= 30
9890.617205.63569902.262 205.4669927.477204.35059933.474203.86749940.503202.8978
9953.528199.84559964.686196.92239966.554 196.3399979.579190.79559992.605187.0243
9995.898185.782210005.63183.9018 10011.5186.995410018.66192.688510027.11195.8791
10031.68196.884310042.72194.328410044.71193.611810057.73187.490310070.76 188.413
10073.93189.115410083.78190.310410096.81193.781610105.14196.281410109.83197.9672
10120.75201.451810122.86201.974910135.89 204.41410148.91 206.18410177.81208.2115
#Mann= 3 , 0 , 0
9890.617  0.0507       09890.617  0.0507       010177.81  0.0507       0
#XS Ineff= 2 , 0
       0                10028.61       0
Bank Sta=9890.617,10177.81
Exp/Cntr=0.3,0.1

Type RM Length L Ch R = 1 ,7825.317,74.749400,74.749400,74.749400
XS GIS Cut Line= 2
994044.277975887 764595.24400045 994193.96747911764451.075831383
#Sta/Elev= 25
9918.366202.50429933.252201.65489947.136200.6677 9961.02198.63289961.964198.3865
9974.903194.2726 9976.38193.58759988.787186.93389990.795185.956810002.67182.6145
10005.21183.101310016.55186.859110019.63186.840410030.44184.507710034.04183.4197
10044.32 181.58710048.46182.219410058.21184.968510062.87186.884210072.09189.7021
10077.29192.151710085.97195.657610099.86199.674410113.74201.724910126.19202.9863
#Mann= 3 , 0 , 0
9918.366   0.055       09918.366   0.055       010126.19   0.055       0
#XS Ineff= 2 , 0
       0                10034.41       0
Bank Sta=9918.366,10126.19
Exp/Cntr=0.3,0.1

Type RM Length L Ch R = 1 ,7750.568,145.568800,145.568800,145.568800
XS GIS Cut Line= 2
994113.021298558764641.906159922994243.229631841764470.031159922
#Sta/Elev= 24
9906.862195.74339928.072 195.597 9943.26194.98899953.163194.12059965.709190.4331
 9976.38 186.7329978.255185.8958  9990.8171.4949 9992.94170.170510003.35171.0208
 10009.5174.683310015.89180.102310026.06187.974910028.44189.425510040.98195.6583
10042.62196.134810053.53197.963310059.18198.378710066.07198.611810078.62199.3483
10091.17199.457710103.71199.673810108.86 199.89210122.49 200.125
#Mann= 3 , 0 , 0
9906.862   0.055       09906.862   0.055       010122.49   0.055       0
#XS Ineff= 2 , 0
       0                10037.71       0
Bank Sta=9906.862,10122.49
Exp/Cntr=0.3,0.1

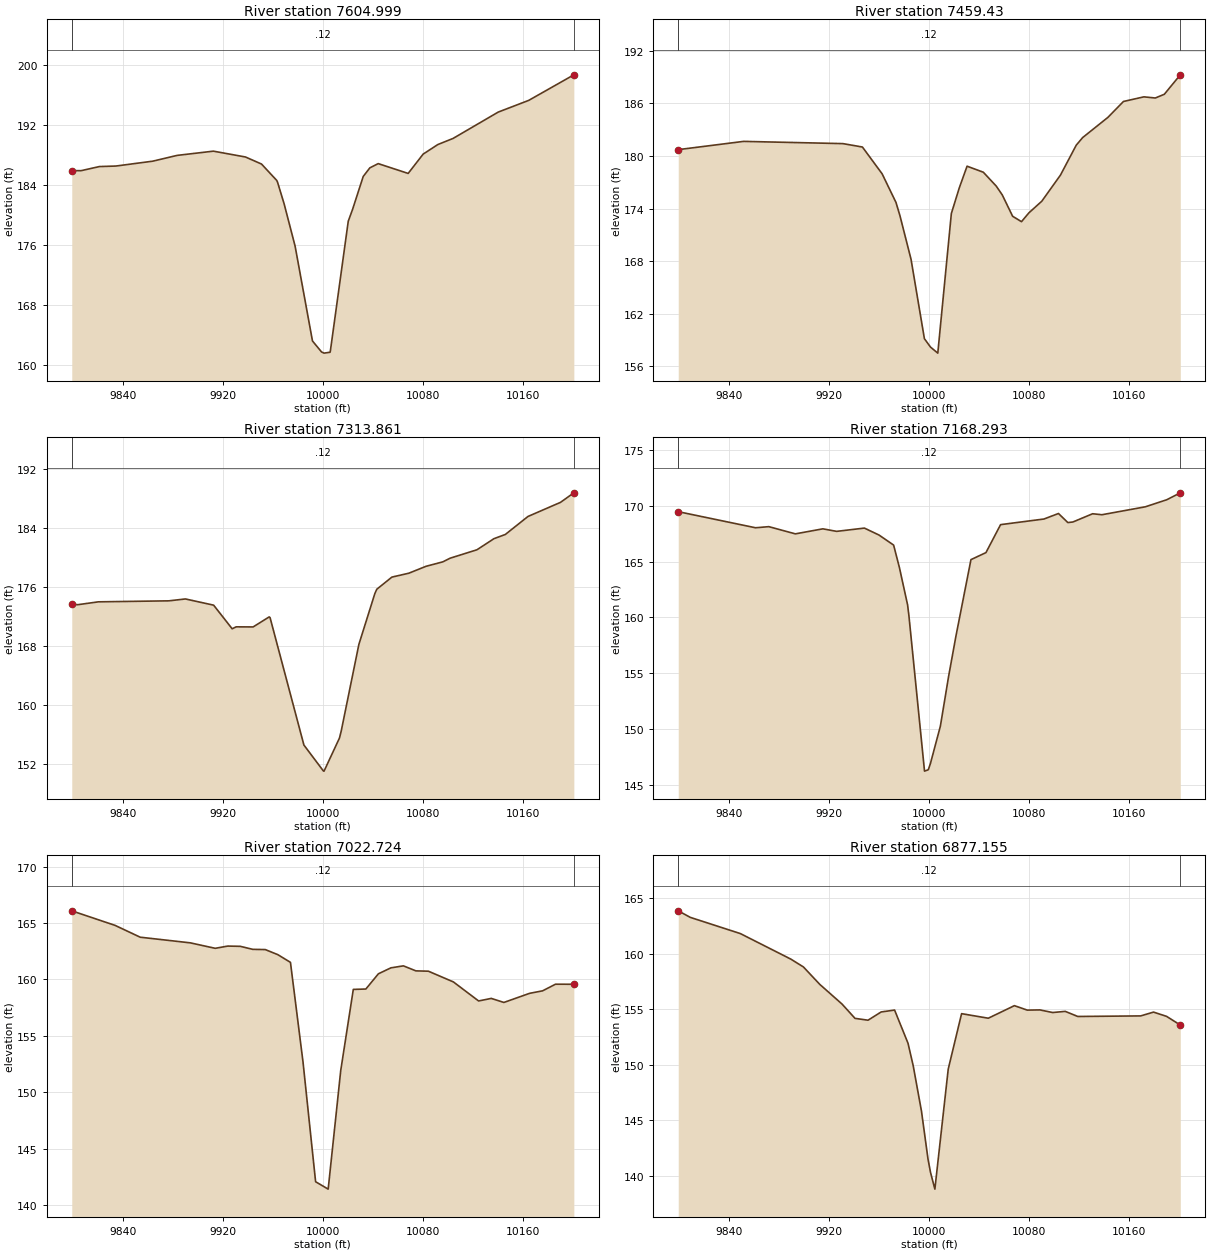
Type RM Length L Ch R = 1 ,7604.999,145.568900,145.568900,145.568900
XS GIS Cut Line= 6
994150.105705034764811.629639787994192.771044203764762.859537523
994258.674899293764680.901574591994297.381731719764642.098813575
994357.979276109764550.504838642994396.652902388764495.456809528
#Sta/Elev= 30
9799.052185.88829806.485185.87519821.147186.42419834.433186.4954 9863.85187.1418
9883.365187.91269912.432188.47729938.096187.69959950.928186.76229963.154184.5709
 9963.76184.34399969.019 181.4689977.818175.82899991.731163.1869    9999161.7221
   10001161.568610005.81 161.685 10006.1161.915510020.37179.145110023.84180.7279
10032.35185.107510037.65186.252310044.34186.816610068.32185.510910080.32188.0822
10092.02189.3545 10104.3190.175210140.39 193.68110164.84195.243110200.94198.6471
#Mann= 3 , 0 , 0
9799.052    0.12       09799.052    0.12       010200.94    0.12       0
#XS Ineff= 2 , 0
       0                               0
Bank Sta=9799.052,10200.94
Exp/Cntr=0.3,0.1

Type RM Length L Ch R = 1 , 7459.43,145.568800,145.568800,145.568800
XS GIS Cut Line= 6
994259.717191031764867.029245638994366.010641924764743.395735758
994383.123630749764730.967751965994417.013249669 764717.60228001
994436.368143862764701.519808235994532.846227262764579.169988663
#Sta/Elev= 30
 9799.13180.71239851.445181.65399930.912 181.399  9946.5181.01069962.253177.9621
9973.363174.69319976.541173.17899985.407168.21459996.091159.1695   10001158.2073
10006.81157.523210017.66173.437110023.92176.320410030.23 178.82610043.23  178.14
10053.57176.560410058.34175.568710066.69173.119810073.78 172.50310079.65173.5016
10090.03174.837710104.95177.811410117.59181.2229 10122.7182.083610142.89184.3861
10155.37186.2011 10171.7186.729410180.83186.597210188.04  187.0210200.85189.2388
#Mann= 3 , 0 , 0
 9799.13    0.12       0 9799.13    0.12       010200.85    0.12       0
#XS Ineff= 2 , 0
       0                               0
Bank Sta=9799.13,10200.85
Exp/Cntr=0.3,0.1

Type RM Length L Ch R = 1 ,7313.861,145.568800,145.568800,145.568800
XS GIS Cut Line= 6
 994364.66620248764927.936410875994392.794325562 764906.42128751
994431.349595075764873.572172848994505.896444766764805.420300389
994546.110648513764764.873740065994661.956065138764657.756715573
#Sta/Elev= 30
9799.023 173.6869803.857173.62939820.316174.01789876.746174.15349890.034174.4094
9912.613 173.5659927.433 170.3649930.681170.62569944.231170.61289957.074171.9716
 9957.78171.87699984.878154.587110000.58151.0501   10001151.050910013.35155.5402
10014.75156.489310028.89168.245210041.64175.123110043.21175.722910055.31 177.372
10068.93 177.90410082.55178.833410096.17179.447210101.94179.938510123.41181.0815
10137.03182.586210146.13183.158410164.27185.599910190.32187.515210200.99188.8077
#Mann= 3 , 0 , 0
9799.023    0.12       09799.023    0.12       010200.99    0.12       0
#XS Ineff= 2 , 0
       0                               0
Bank Sta=9799.023,10200.99
Exp/Cntr=0.3,0.1

Type RM Length L Ch R = 1 ,7168.293,145.568800,145.568800,145.568800
XS GIS Cut Line= 6
994396.818564971765008.851870123994486.039170519 764976.58714841
994532.433859298764955.056302609994558.975603137764938.939864478
994617.949033464764896.341704175994749.176697931764819.529202083
#Sta/Elev= 30
9799.059169.48369860.928168.04129871.562168.1407 9892.83167.49489914.838 167.945
9925.862167.71849948.084168.01159959.783167.38979971.483166.48759976.134164.4688
9982.666161.12779983.686160.20039996.223146.22759999.232146.3511   10001146.9282
10008.91150.261510015.46154.694410021.39158.344910033.39165.184910045.39165.8135
 10057.1168.320610091.86 168.82610103.45169.319710110.97 168.50510115.03168.5597
10130.77169.296910138.21169.208810172.97169.919410190.15170.553610200.98171.1728
#Mann= 3 , 0 , 0
9799.059    0.12       09799.059    0.12       010200.98    0.12       0
#XS Ineff= 2 , 0
       0                               0
Bank Sta=9799.059,10200.98
Exp/Cntr=0.3,0.1

Type RM Length L Ch R = 1 ,7022.724,145.568900,145.568900,145.568900
XS GIS Cut Line= 6
994420.483051976765054.749858472994533.268461689765047.783522889
994661.388431721765059.897961526 994704.39478381 765060.75707698
994767.057006893765053.551581471994819.181712037765039.773261727
#Sta/Elev= 30
9799.042166.08749833.729164.79669853.827163.74849893.867 163.2499913.872162.7639
9923.888 162.9619933.903162.93959943.919162.67179953.956 162.6519964.023162.1984
9974.091 161.5189984.159 152.6689994.227142.065110004.29141.409810014.34151.9319
 10024.4159.119310034.45159.153410044.48160.503410054.49161.030710064.49161.2074
10074.49160.762710084.49160.734110104.54159.781210124.71158.094310134.82158.3216
10144.93157.963110165.57158.772510175.91 158.99310186.26159.580210200.93159.5759
#Mann= 3 , 0 , 0
9799.042    0.12       09799.042    0.12       010200.93    0.12       0
#XS Ineff= 2 , 0
       0                               0
Bank Sta=9799.042,10200.93
Exp/Cntr=0.3,0.1

Type RM Length L Ch R = 1 ,6877.155,145.568800,145.568800,145.568800
XS GIS Cut Line= 6
994375.309850234765153.544287229994438.074299821765153.762965402
994487.896485356765161.495205765994662.765496767765218.333175473
994710.220007905765219.401359197994765.521001659765206.730126571
#Sta/Elev= 30
9799.089163.88089808.783163.28879848.811161.8292 9889.15159.53029899.269158.8217
 9912.32157.25499930.147 155.4799940.569154.18499950.992154.01869961.505154.7618
9972.254154.93259983.002151.93739987.108149.93399993.751145.8291    9999141.4924
   10001140.295710004.49138.787710015.18149.611610025.87154.608810047.24154.1975
10068.14155.330410078.43154.927410088.62154.946410098.78154.709210108.82154.8151
10118.85154.354610169.23154.405910179.49154.748710189.93154.365210200.92153.5822
#Mann= 3 , 0 , 0
9799.089    0.12       09799.089    0.12       010200.92    0.12       0
#XS Ineff= 2 , 0
       0                               0
Bank Sta=9799.089,10200.92
Exp/Cntr=0.3,0.1

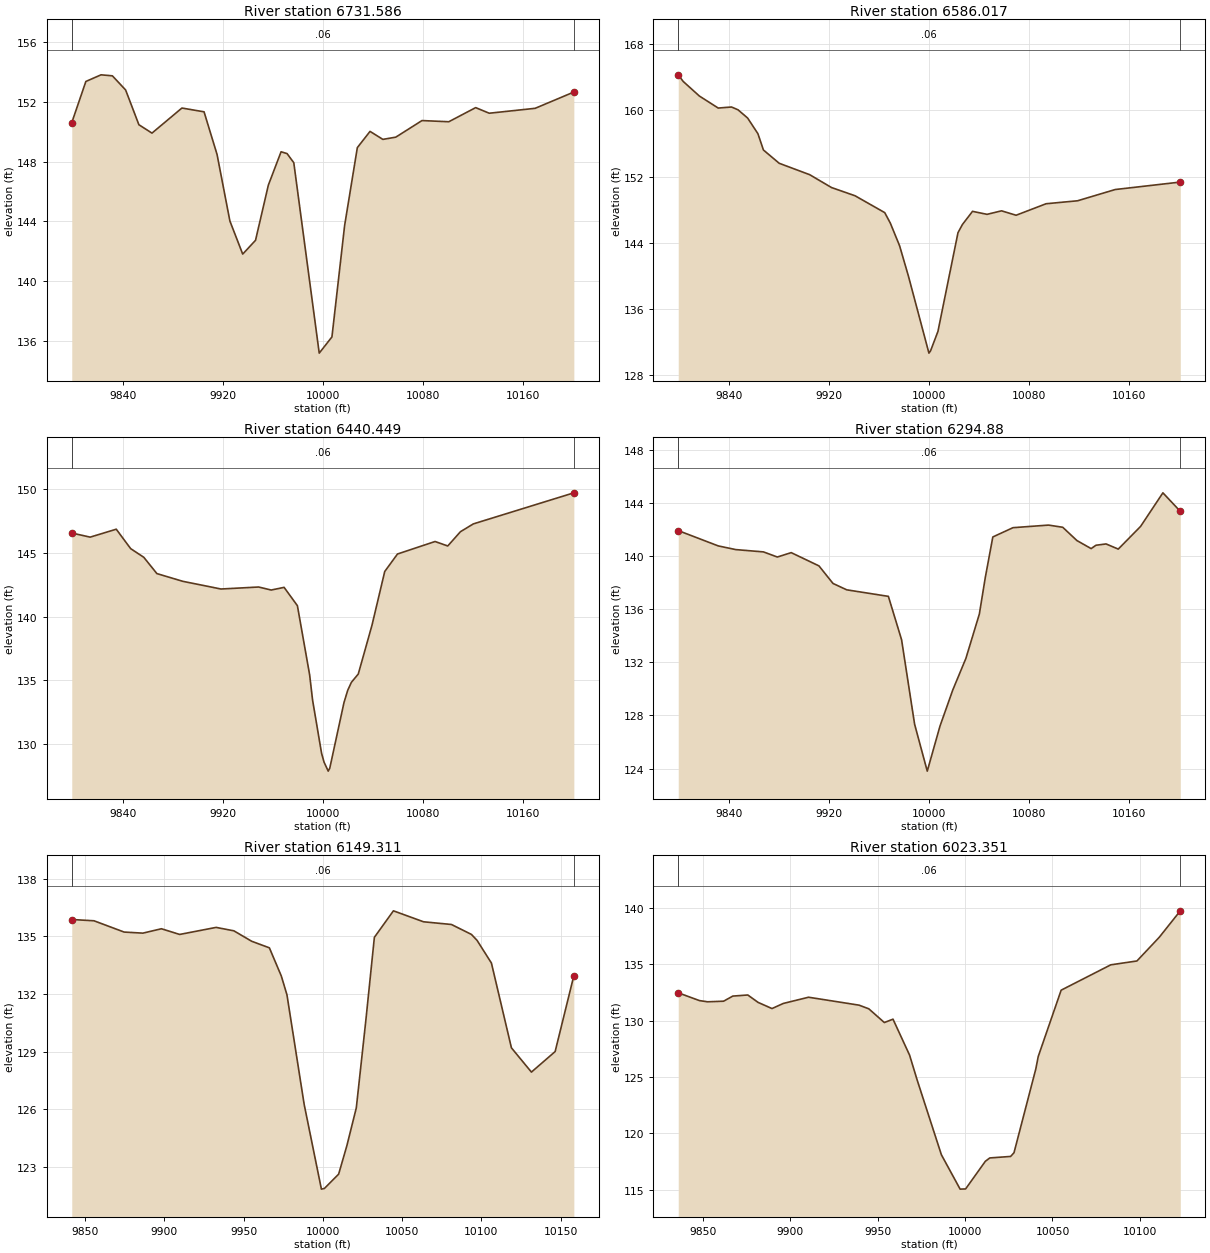
Type RM Length L Ch R = 1 ,6731.586,145.568800,145.568800,145.568800
XS GIS Cut Line= 6
994354.364275938765382.828241207994408.043389675765363.786735475
994464.990581009765347.088938401994618.875123819765314.096937588
994672.087487111765293.217958107994735.295975759765260.903799131
#Sta/Elev= 30
9799.021150.62249810.306153.38429822.436153.82939831.527153.76189842.137152.8141
9852.748150.48479863.227149.92259887.206151.60349904.911151.34939915.332148.4894
9925.596144.0324 9935.86 141.8139946.125142.73849956.389146.43729966.575148.6725
9971.361148.55049976.754147.93779997.111135.175710007.29136.261310017.45143.7347
10027.62148.949510037.78150.038110048.07149.502110058.42149.652210079.36150.7633
10100.84150.684610122.33151.630710133.21151.255410169.96151.584510200.93152.6754
#Mann= 3 , 0 , 0
9799.021    0.06       09799.021    0.06       010200.93    0.06       0
#XS Ineff= 2 , 0
       09969.749                       0
Bank Sta=9799.021,10200.93
Exp/Cntr=0.3,0.1

Type RM Length L Ch R = 1 ,6586.017,145.568800,145.568800,145.568800
XS GIS Cut Line= 6
 994524.81247163765588.113572087994564.372557226765539.435108832
994599.499898986765490.855487671994697.314241095765334.587228222
 994727.36282224765299.256811724994762.935145924765266.358973699
#Sta/Elev= 30
9799.022164.30549803.034163.4981 9815.92161.74239831.031 160.2849841.691 160.411
9846.887160.07269854.577159.07579862.819157.17869867.221155.20759879.885153.5968
9904.242152.22099921.697150.66589940.552  149.679964.334147.62729968.822146.3532
9976.226143.61599983.375 139.9029999.718130.6246   10001 130.89710006.92133.2478
10022.97145.201910026.53146.1927 10034.6147.783410046.22147.420710057.85147.8454
10069.48147.311210093.52148.704110118.69149.061310148.84150.423610200.94151.3262
#Mann= 3 , 0 , 0
9799.022    0.06       09799.022    0.06       010200.94    0.06       0
#XS Ineff= 2 , 0
       0                               0
Bank Sta=9799.022,10200.94
Exp/Cntr=0.3,0.1

Type RM Length L Ch R = 1 ,6440.449,145.568900,145.568900,145.568900
XS GIS Cut Line= 6
994751.366368342765658.612420347994787.815596623765523.003156405
994780.556744288765485.972775925994748.573299063765436.480059341
994744.185437965765387.737663916994786.986966723765283.846742424
#Sta/Elev= 30
9799.157 146.5599813.893146.23689834.747 146.8599846.273145.33259856.765144.6528
9867.258143.37179887.982142.76449918.524142.16029948.614142.31729958.669142.0799
9969.007142.28929979.643140.8516 9989.41135.43239991.813133.4173    9999129.2425
   10001128.547510004.31127.849810005.53128.078110016.91133.235110019.89134.1981
10022.84134.827810028.35135.4823 10039.3139.311710049.51143.537910059.72144.9111
10089.77145.892410099.92145.541210110.07146.6625 10120.4147.276910200.78149.7182
#Mann= 3 , 0 , 0
9799.157    0.06       09799.157    0.06       010200.78    0.06       0
#XS Ineff= 2 , 0
       0                               0
Bank Sta=9799.157,10200.78
Exp/Cntr=0.3,0.1

Type RM Length L Ch R = 1 , 6294.88,145.568800,145.568800,145.568800
XS GIS Cut Line= 6
994811.064848735765666.400050121994884.872227204765513.782719725
994897.146835181765460.084717163 994913.27148232765420.026411887
994944.024303088765363.142325736994982.801357478765305.775849269
#Sta/Elev= 30
9799.053141.9135 9831.06140.7604 9845.04140.48319867.256140.30879878.364139.9232
9889.472140.25349911.688139.25519922.936137.93189933.904137.45399967.228136.9622
9977.807 133.6969988.231127.33439998.354123.806810008.53127.194410018.75129.9095
10029.26132.289210040.04135.630310044.81 138.38810050.82141.433210066.96 142.132
10095.41142.327110106.78142.162110118.15141.161510129.51140.556810133.37140.8098
10141.45140.907810151.22140.520210169.08142.226310186.94144.755610200.87143.3611
#Mann= 3 , 0 , 0
9799.053    0.06       09799.053    0.06       010200.87    0.06       0
#XS Ineff= 2 , 0
       0                10074.34       0
Bank Sta=9799.053,10200.87
Exp/Cntr=0.3,0.1

Type RM Length L Ch R = 1 ,6149.311,125.959700,125.959700,125.959700
XS GIS Cut Line= 6
994917.517998143765702.917161792994945.424258397765658.753354379
994965.095356091765624.104102463995008.503321539765533.275414563
 995033.18155284765497.571448514995082.187280711765433.772076385
#Sta/Elev= 30
9841.656135.87689855.663135.81089874.679135.22379886.508135.16789898.214 135.396
9909.713135.09979932.711135.46689943.926135.28769955.113134.7459  9966.3134.4026
 9973.84132.93379977.381131.95879988.245126.25469999.108121.8499   10001121.8847
10009.98122.6294 10015.2124.117710021.13126.080710027.15130.638310032.52  134.95
10044.54136.3286 10063.5135.758610081.13135.617710093.74135.101110097.29134.7916
10106.35133.610810118.96129.200910131.57127.938410146.53129.006110158.33132.9526
#Mann= 3 , 0 , 0
9841.656    0.06       09841.656    0.06       010158.33    0.06       0
#XS Ineff= 2 , 0
       0                10055.81       0
Bank Sta=9841.656,10158.33
Exp/Cntr=0.3,0.1

Type RM Length L Ch R = 1 ,6023.351,150.040300,150.040300,150.040300
XS GIS Cut Line= 2
994993.396093935765733.747620881995192.180816174765526.282343119
#Sta/Elev= 30
9835.844132.46289847.959131.77169852.616131.66429861.808131.7176 9867.07132.1706
9875.658132.26859881.525131.61249889.507131.06499895.979131.51899910.433132.0696
9939.342131.36589944.905131.04179953.796129.82469958.754130.1237 9968.25126.9313
9972.604124.71299986.453118.09469997.158115.0516 10000.3115.068810011.61117.5227
10014.15117.817110026.07117.9505   10028118.282210040.52125.736910041.85126.8063
10054.98132.6948 10083.4134.943910098.34135.2845 10111.1 137.38210123.17139.7319
#Mann= 3 , 0 , 0
9835.844    0.06       09835.844    0.06       010123.17    0.06       0
#XS Ineff= 2 , 0
       0                10037.32       0
Bank Sta=9835.844,10123.17
Exp/Cntr=0.3,0.1

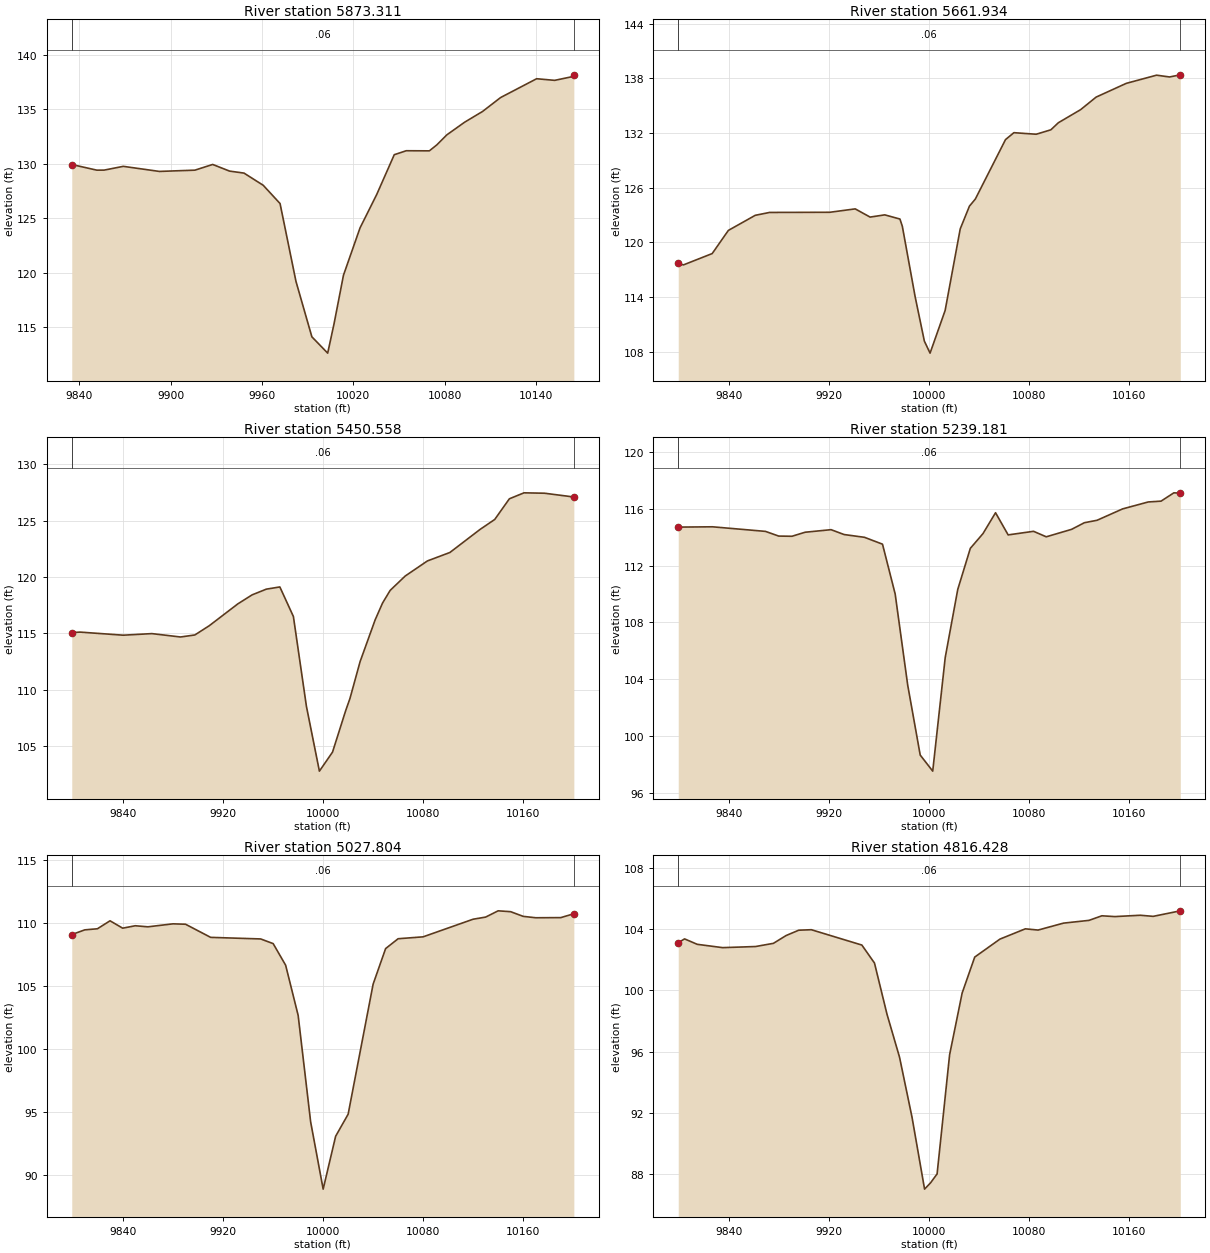
Type RM Length L Ch R = 1 ,5873.311,211.376600,211.376600,211.376600
XS GIS Cut Line= 6
995027.616904693765824.478803469995104.607739497 765774.00820315
995144.432152437765755.100650718 995185.30638596765743.294603387
995204.177992421765735.127754232995315.639878895765667.470681635
#Sta/Elev= 30
9835.153129.9161 9851.62129.3969 9856.41129.40089868.994129.74739892.668129.2805
 9916.04129.39699927.701129.92069938.771 129.3119948.271129.12719960.911128.0068
9971.945 126.3339982.393119.1914 9992.84114.099410003.23112.602410007.39115.2854
10013.59119.753110024.47124.097110035.42127.161410046.95130.815710054.82131.1795
   10070131.169310074.91131.718610081.53132.642710093.12133.794810104.95134.7859
10116.79136.062610140.46137.789510152.29  137.6410164.13137.987410164.89138.1477
#Mann= 3 , 0 , 0
9835.153    0.06       09835.153    0.06       010164.89    0.06       0
#XS Ineff= 2 , 0
       0                               0
Bank Sta=9835.153,10164.89
Exp/Cntr=0.3,0.1

Type RM Length L Ch R = 1 ,5661.934,211.376600,211.376600,211.376600
XS GIS Cut Line= 5
995111.336995377766014.758655788995251.058297704765935.702098481
 995283.50427955765913.337726658995285.325012504765912.510120767
995450.725524642765800.158353173
#Sta/Elev= 30
9799.057117.68599803.265117.52999826.245118.7725 9839.18121.31259860.714122.9704
9872.204 123.2869920.406 123.3039940.712123.67639952.632122.7756 9964.38123.0194
9976.526122.56149978.451121.75959988.671114.05069996.071109.164910000.64107.8452
 10012.7 112.52710024.78121.479810032.16123.977210036.87124.754510061.05131.2834
10067.76132.039310085.55131.867510097.32132.353410103.35133.131510121.15134.5661
10133.58 135.94510157.76137.454910181.94138.350510192.33138.153610200.95138.3886
#Mann= 3 , 0 , 0
9799.057    0.06       09799.057    0.06       010200.95    0.06       0
#XS Ineff= 2 , 0
       0                               0
Bank Sta=9799.057,10200.95
Exp/Cntr=0.3,0.1

Type RM Length L Ch R = 1 ,5450.558,211.376700,211.376700,211.376700
XS GIS Cut Line= 6
 995179.05864734766167.106699536995313.313727226766091.879508953
995335.727007404766082.547588397995378.264204585766069.507434777
995456.549891133766017.044369733 995529.04374144765972.777768332
#Sta/Elev= 30
9799.043115.06939805.854115.10649840.243114.83339863.168114.97319886.094114.6742
9897.557114.8537 9909.02115.66669931.945117.60799943.408118.40939954.765118.9149
9965.597119.10999976.429116.49159986.855108.53129997.249 102.78310007.74104.4655
10018.28108.145810021.72 109.22910029.83112.494310041.87116.193810047.78117.6817
 10053.9118.806710065.94120.0791 10083.7121.416410101.67122.164210125.86124.2112
10137.58125.092510149.29126.923210161.01127.453610177.45127.4184 10200.9127.0836
#Mann= 3 , 0 , 0
9799.043    0.06       09799.043    0.06       0 10200.9    0.06       0
#XS Ineff= 2 , 0
       0                               0
Bank Sta=9799.043,10200.9
Exp/Cntr=0.3,0.1

Type RM Length L Ch R = 1 ,5239.181,211.376600,211.376600,211.376600
XS GIS Cut Line= 6
995269.148573047766271.328536844995358.618690208766239.737884733
995407.751729464766225.509532822995436.116060765766220.739329561
995524.131574616766212.859368019995660.030219322766185.273255517
#Sta/Elev= 30
9799.048114.70619826.464114.72729868.884114.40499879.489114.07429890.094114.0608
9900.575114.34459921.397114.52549931.808114.18279948.156113.98729962.574113.5048
9972.715109.99819982.747103.58549992.76598.6593610002.7897.5274910012.79105.5303
10022.81110.315710032.89 113.21210042.98114.244410053.07115.717410063.16114.1576
 10083.5114.409910093.66114.022810113.99114.549810124.16115.014510134.34115.1868
10154.84 115.98910175.33116.476510185.58116.534110195.82117.119210200.98117.0947
#Mann= 3 , 0 , 0
9799.048    0.06       09799.048    0.06       010200.98    0.06       0
#XS Ineff= 2 , 0
       0                               0
Bank Sta=9799.048,10200.98
Exp/Cntr=0.3,0.1

Type RM Length L Ch R = 1 ,5027.804,211.376600,211.376600,211.376600
XS GIS Cut Line= 6
995254.701546389766438.991446991995313.448660877 766430.16990758
995366.926786242766425.208315159995458.533362517 766421.65233224
995570.048891348766420.025206894995655.439682633766413.548562284
#Sta/Elev= 30
9799.021109.05099809.435109.42539819.547109.51189829.659110.14339839.771109.5597
9849.883109.75079859.985109.6659 9880.07109.90229890.113 109.8719910.199108.8307
9950.237108.70569960.245108.33669970.253106.62269980.261102.64689990.26894.20617
10000.2888.8796210010.2893.0728210020.2894.8161910040.28105.124710050.28107.9418
10060.28108.721810080.29108.8722 10120.3 110.26810130.33110.436310140.36110.9337
10150.39110.864910160.42110.495110170.45110.3843 10190.5110.395710200.97110.7025
#Mann= 3 , 0 , 0
9799.021    0.06       09799.021    0.06       010200.97    0.06       0
#XS Ineff= 2 , 0
       0                               0
Bank Sta=9799.021,10200.97
Exp/Cntr=0.3,0.1

Type RM Length L Ch R = 1 ,4816.428,211.376600,211.376600,211.376600
XS GIS Cut Line= 6
995290.015331384766656.008400086995443.486148432766630.579165051
995473.592196319766628.306650728 995508.61200695766630.062536222
995538.546161796766626.741196871995686.115433799766595.191393923
#Sta/Elev= 30
9799.036103.12489804.101103.37699814.263103.02089834.587 102.8049860.928102.8763
9875.235103.08559885.355103.59419895.468103.94429905.581103.97659946.034102.9727
9956.134101.79619966.16298.444499976.19195.636819986.218 91.69369996.23587.00397
   1000187.4134110006.2687.9992910016.2795.7946110026.3199.8340810036.37102.1856
10056.56103.3618 10076.9104.034810087.08103.953510107.42104.407110127.87104.5882
10138.15104.887310148.42104.835410168.97104.922410179.25104.850810200.95105.2125
#Mann= 3 , 0 , 0
9799.036    0.06       09799.036    0.06       010200.95    0.06       0
#XS Ineff= 2 , 0
       0                               0
Bank Sta=9799.036,10200.95
Exp/Cntr=0.3,0.1