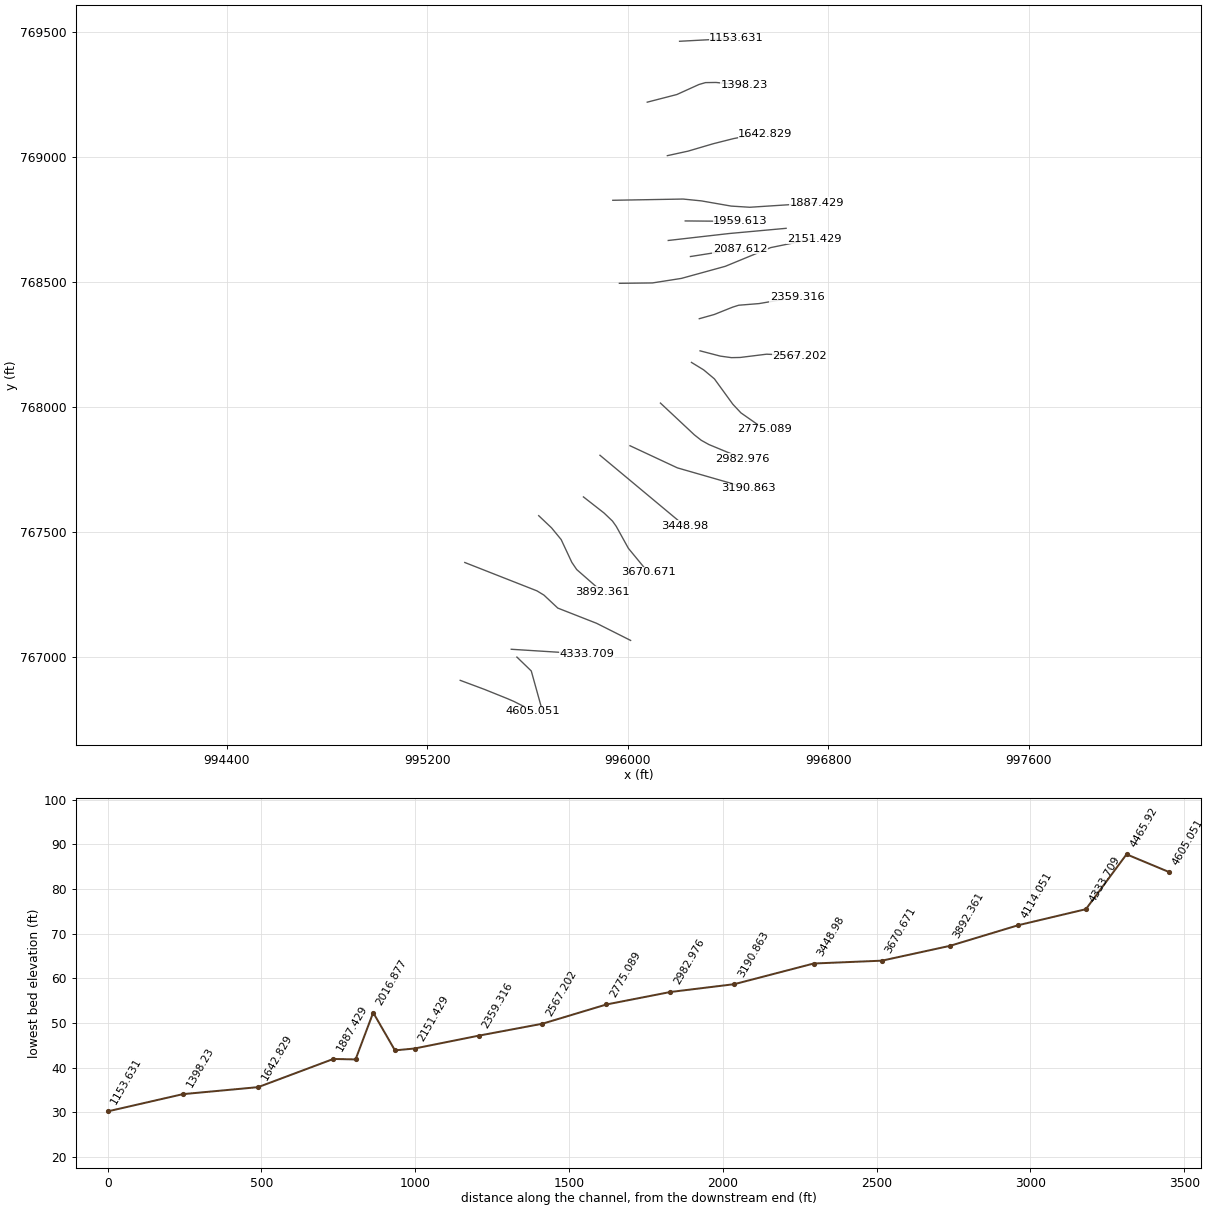
HEC-RAS study 156_ras.prj: 156

--- 156_ras.g01 (geometry) --- (continued)

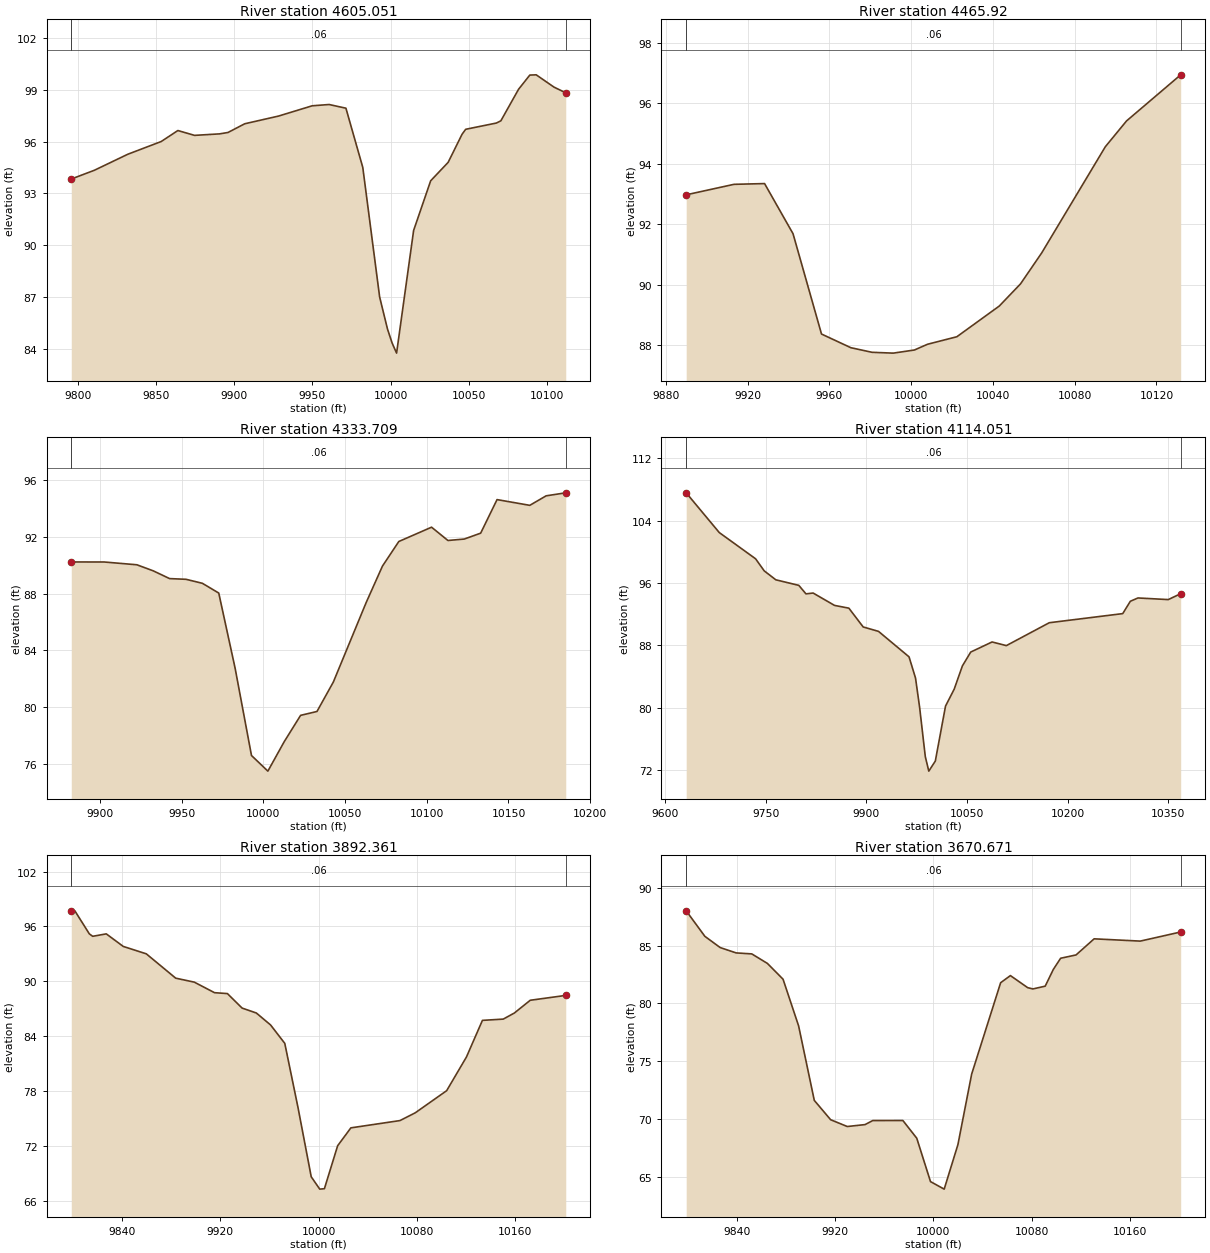
Type RM Length L Ch R = 1 ,4605.051,139.131300,139.131300,139.131300
XS GIS Cut Line= 6
995331.138468891  766908.2314073995428.580300301766871.760524496
995520.570289522766834.634169281995545.484782934766823.813591272
995575.978167027766808.409660637 995621.70185411766784.267271027
#Sta/Elev= 30
9795.75793.832699810.55894.340199831.91395.266359853.26896.002349863.94596.63877
9874.62396.358499890.55996.444869895.97896.525179906.72397.030169928.29197.47484
9949.858 98.06979960.64298.144239971.426  97.9319982.20994.505849992.99387.00785
9998.023 85.1493   10001 84.339110003.8383.7595310014.7390.8584510025.6393.73088
10036.8294.7982110045.7196.4235510048.0396.7102310067.6397.0714510070.5397.20091
10081.8499.0254310089.0599.8474510093.1499.8618110104.4599.1541610112.0398.82032
#Mann= 3 , 0 , 0
9795.757    0.06       09795.757    0.06       010112.03    0.06       0
#XS Ineff= 2 , 0
       0                               0
Bank Sta=9795.757,10112.03
Exp/Cntr=0.3,0.1

Type RM Length L Ch R = 1 , 4465.92,132.210900,132.210900,132.210900
XS GIS Cut Line= 3
995557.465742975767001.281159908995614.757409632 766945.72560437
995658.160187453 766789.47560437
#Sta/Elev= 17
9889.87992.974249913.26793.320379928.23393.345199942.16391.689199956.09288.37811
9970.43787.927159980.81687.774779991.19487.7477310001.5787.8507710007.9588.04001
10022.3388.2889510043.0989.3027610053.4790.0337610063.8491.0560310094.9894.56202
10105.3695.4139110131.8596.93568
#Mann= 3 , 0 , 0
9889.879    0.06       09889.879    0.06       010131.85    0.06       0
#XS Ineff= 2 , 0
       0                               0
Bank Sta=9889.879,10131.85
Exp/Cntr=0.3,0.1

Type RM Length L Ch R = 1 ,4333.709,219.657800,219.657800,219.657800
XS GIS Cut Line= 2
995534.896298521767032.531159914995836.979631864767013.433937705
#Sta/Elev= 26
9882.37390.234159902.516 90.23269922.55690.035449932.57689.606849942.59689.06009
9952.61689.010769962.63688.728479972.65688.040429982.67682.733559992.69676.57433
10002.7275.4718910012.7477.5524910022.76  79.40810032.7879.68252 10042.881.76086
10062.8487.3567210072.8689.9423210082.8891.6789610102.9292.6883210112.9491.74995
10122.9691.8518910132.9892.26806   1014394.6356510163.0494.2312110173.0694.90274
10185.0695.11414
#Mann= 3 , 0 , 0
9882.373    0.06       09882.373    0.06       010185.06    0.06       0
#XS Ineff= 2 , 0
       0                               0
Bank Sta=9882.373,10185.06
Exp/Cntr=0.3,0.1

Type RM Length L Ch R = 1 ,4114.051,221.690300,221.690300,221.690300
XS GIS Cut Line= 6
 995349.42612661767379.622410156995637.664477188767266.095950266
995665.508072575767249.039064587995720.570412202767197.303502401
995875.557401931767136.393736303996011.335366214767067.909323885
#Sta/Elev= 30
9631.323107.55669680.671102.46159734.81299.102719747.66197.554659764.944 96.4098
9799.24495.697899809.90594.608119820.56794.71449 9852.5593.127679873.87392.77704
9895.19590.368939918.07889.801249963.59586.537419973.269 83.81749979.40680.04161
9987.83973.752499993.05571.8928310002.7973.18654   1001880.2285410030.9482.40044
10043.1485.3757610055.5987.15275 10087.488.44469 10108.787.9775410172.68 90.9091
10282.2292.0781310293.54 93.657810304.8694.0827310350.14 93.875910368.6394.63079
#Mann= 3 , 0 , 0
9631.323    0.06       09631.323    0.06       010368.63    0.06       0
#XS Ineff= 2 , 0
       0                               0
Bank Sta=9631.323,10368.63
Exp/Cntr=0.3,0.1

Type RM Length L Ch R = 1 ,3892.361,221.690300,221.690300,221.690300
XS GIS Cut Line= 6
995644.371614928767567.002001549995695.801310252767518.129039561
995733.988910708767471.510712282995776.660694987767380.238400311
995796.116075333767351.461230929995897.267552293767262.703360401
#Sta/Elev= 30
9799.10997.694219802.01697.704189813.77195.189629816.53294.920089827.56695.18492
9841.36193.811989860.08393.001949883.97290.343669899.09889.907679915.49788.75645
9925.97888.657819937.90787.07405  9949.586.534659961.093 85.22429972.59683.21691
9983.34276.201919994.08868.63316   1000167.28309 10004.867.3299810015.5572.02465
 10026.373.9797910066.22 74.777510078.6275.6258910104.1378.0436210120.2481.73316
10133.1985.7299910150.0985.86783 10159.186.5297410172.0587.92712 10200.988.45906
#Mann= 3 , 0 , 0
9799.109    0.06       09799.109    0.06       0 10200.9    0.06       0
#XS Ineff= 2 , 0
       0                               0
Bank Sta=9799.109,10200.9
Exp/Cntr=0.3,0.1

Type RM Length L Ch R = 1 ,3670.671,221.690300,221.690300,221.690300
XS GIS Cut Line= 6
995823.053807731 767642.03181055995905.332482556767577.562361586
995938.853303628767545.517396331995953.969948571767524.206379237
996002.430526107 767436.35503081996081.337505797767340.365106633
#Sta/Elev= 30
9799.06788.003439814.24385.800329826.68184.829389839.65184.367699852.35684.28219
 9865.0683.460089877.76482.096969890.46878.044919903.17271.626289916.46169.95486
9929.98569.368349944.44169.534569950.64669.882179975.16669.889179986.44168.35784
 9997.6364.6075310008.7463.95935 10019.967.8060410031.0673.8964210054.6281.79276
10062.5482.4085910076.5981.3654910080.8581.2558310090.8381.4943210097.4382.93978
10103.3783.90582 10115.984.1921710130.5985.5837810168.0985.3874410200.9486.17522
#Mann= 3 , 0 , 0
9799.067    0.06       09799.067    0.06       010200.94    0.06       0
#XS Ineff= 2 , 0
       0                               0
Bank Sta=9799.067,10200.94
Exp/Cntr=0.3,0.1

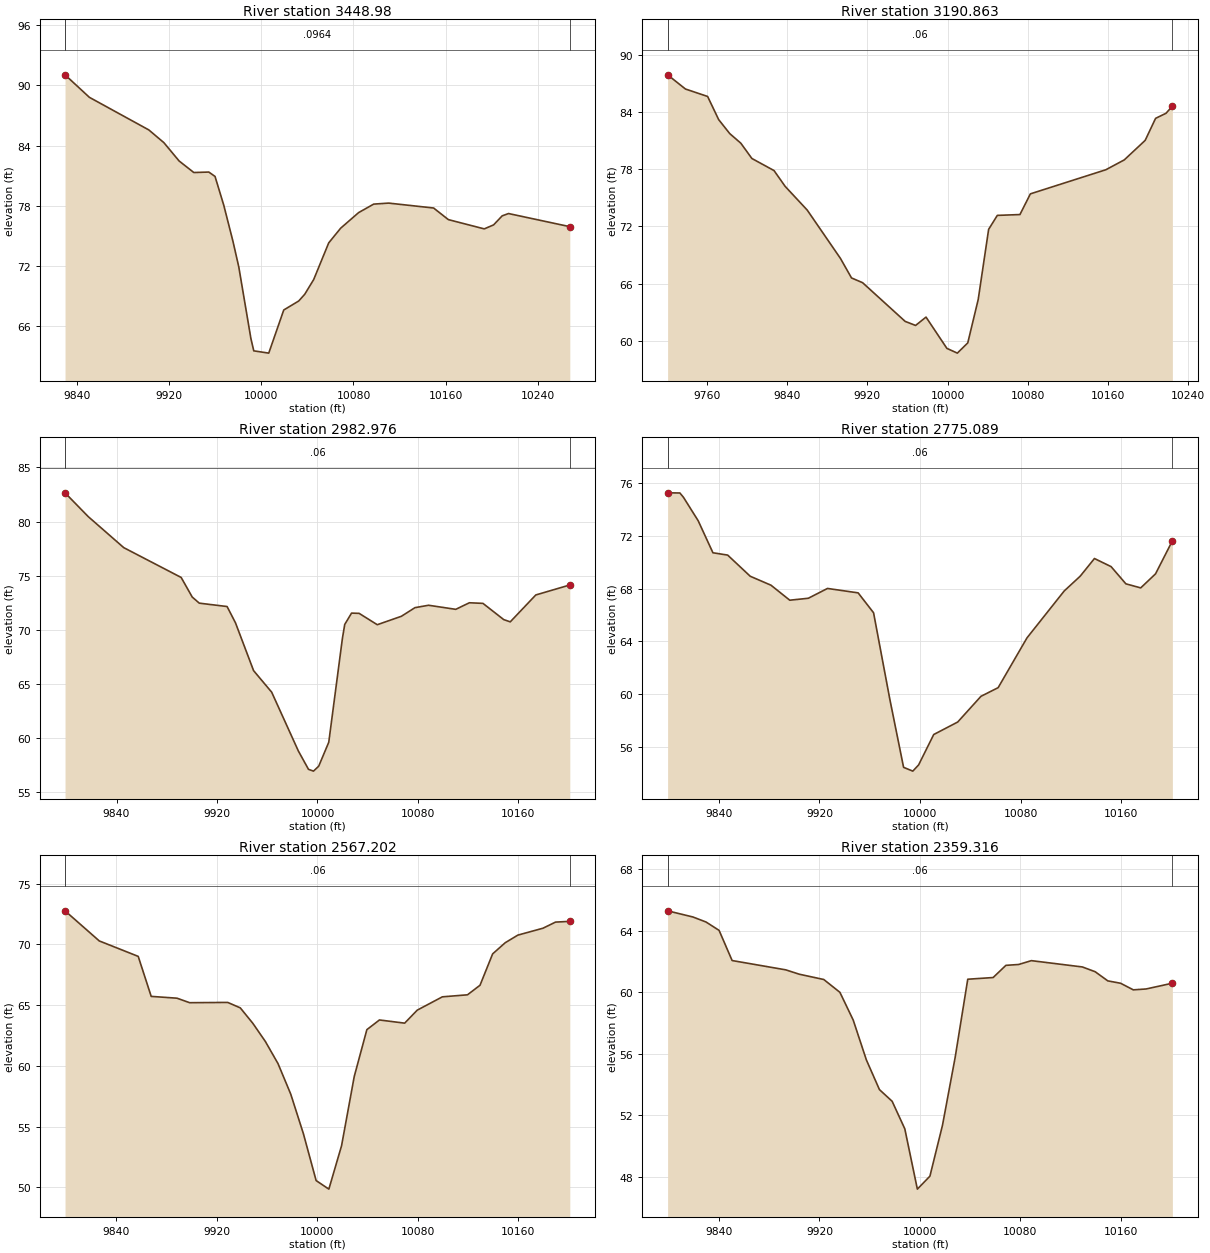
Type RM Length L Ch R = 1 , 3448.98,258.117200,258.117200,258.117200
XS GIS Cut Line= 2
995889.062965184767808.572826579996225.868520766767527.322826564
#Sta/Elev= 30
9829.26491.04108 9850.4488.800139902.13985.551189915.16884.288619928.44882.46034
9941.22481.309839954.25281.357729959.65180.92435 9967.2878.043259975.25274.45303
9980.30871.911199990.85464.768369993.33663.5510110006.3663.3238210019.3967.61833
10032.4268.5165210037.6669.1883110045.4570.6589310058.4874.3014710068.8675.76524
10084.4677.3174110097.5678.1644110110.5978.2657510149.6777.7755310162.47 76.6212
10193.6775.6979110201.7976.0942910209.28 76.996210214.8177.2256710268.0675.91874
#Mann= 3 , 0 , 0
9829.264  0.0964       09829.264  0.0964       010268.06  0.0964       0
#XS Ineff= 2 , 0
       0                               0
Bank Sta=9829.264,10268.06
Exp/Cntr=0.3,0.1

Type RM Length L Ch R = 1 ,3190.863,207.886900,207.886900,207.886900
XS GIS Cut Line= 3
996008.854631841767846.767271012996198.090742975 767758.22560437
 996481.07685411767676.628382131
#Sta/Elev= 30
9720.70887.888889738.53386.399569760.61485.621129771.65583.191379782.69581.72494
9793.73680.719769804.776 79.11519826.85777.848679837.89776.198769859.97873.70316
  9893.168.63542 9904.1466.589039915.18166.090719957.63962.031949968.04761.60617
9978.45462.482769999.26959.2016910009.6858.7037710020.0859.7773110030.49 64.3232
 10040.9 71.685410049.5673.1486110072.1273.2353810082.5375.4062510157.8477.93631
10176.1978.9688210197.0181.0128310207.4283.3254310217.8283.8572110224.1584.60435
#Mann= 3 , 0 , 0
9720.708    0.06       09720.708    0.06       010224.15    0.06       0
#XS Ineff= 2 , 0
       0                               0
Bank Sta=9720.708,10224.15
Exp/Cntr=0.3,0.1

Type RM Length L Ch R = 1 ,2982.976,207.886800,207.886800,207.886800
XS GIS Cut Line= 6
996130.430829129768017.417599691 996265.87132671767890.270208336
996293.399106093767868.543619737996323.703745991767851.590817033
996410.273278662767815.742082746996458.030313026 767793.62004429
#Sta/Elev= 30
 9799.0182.656459817.45180.46334 9845.7777.593879891.48574.838599900.28873.03184
  9905.972.465819928.055  72.1549934.73270.649149949.14866.234419963.56464.24225
9984.79858.812119992.87557.116679996.84556.95181   1000157.4074810009.0159.61962
10019.8969.2246310021.7270.4990710027.1571.5473910033.1871.5233110047.63 70.4747
10066.8471.2539310077.6672.0507510088.4972.2715810110.1371.8952810120.9672.50153
10131.7872.4461410148.3170.9478210153.5270.7389810173.8773.2237710200.94 74.1444
#Mann= 3 , 0 , 0
 9799.01    0.06       0 9799.01    0.06       010200.94    0.06       0
#XS Ineff= 2 , 0
       0                               0
Bank Sta=9799.01,10200.94
Exp/Cntr=0.3,0.1

Type RM Length L Ch R = 1 ,2775.089,207.886900,207.886900,207.886900
XS GIS Cut Line= 6
996254.243044544768180.118791573996302.796269355768150.338555816
996345.793236722768114.355309164996419.412006957768012.801179575
996451.744826358767978.209483182996546.368109483767911.931254961
#Sta/Elev= 30
9799.10475.260299808.894 75.24859811.723 74.92239823.45473.143289835.18570.71552
9846.917 70.53929864.87768.934629881.38768.256239896.358 67.11889911.111 67.2666
9926.37568.010559950.756 67.67519963.03866.167399975.99559.601519986.93254.44728
9994.27154.160379998.87954.6294710010.9156.9346710030.01 57.8829 10048.559.83107
10062.1960.4883810085.1764.2668710114.7767.81879 10127.5 68.940410138.8470.27925
10152.0769.6658910163.8668.3605910175.6668.0532310187.4569.1160410200.8671.62142
#Mann= 3 , 0 , 0
9799.104    0.06       09799.104    0.06       010200.86    0.06       0
#XS Ineff= 2 , 0
       0                               0
Bank Sta=9799.104,10200.86
Exp/Cntr=0.3,0.1

Type RM Length L Ch R = 1 ,2567.202,207.886800,207.886800,207.886800
XS GIS Cut Line= 6
 996288.62158694768226.414397839996369.269052051768205.358706022
996413.640362979768199.195269453 996448.55312222768199.896474346
996553.899060528768212.955926227996686.320130637768207.724256094
#Sta/Elev= 30
  9799.172.769649826.36370.291489857.36969.018979867.70465.726569888.237 65.5771
9898.33365.206139928.60965.228739938.61164.782129948.61363.509429958.61562.01068
9968.68560.187349978.79357.682499988.90154.41324 9999.0150.5625810009.1449.85842
10019.2553.4279510029.3759.13968 10039.462.9867810049.4363.7842610069.4963.52221
10079.4964.5919110099.4965.6881210119.4965.85503 10129.566.6443410139.5269.22319
10149.54 70.142410159.5670.76833 10179.671.3375610189.6271.8423410200.9771.90111
#Mann= 3 , 0 , 0
  9799.1    0.06       0  9799.1    0.06       010200.97    0.06       0
#XS Ineff= 2 , 0
       0                               0
Bank Sta=9799.1,10200.97
Exp/Cntr=0.3,0.1

Type RM Length L Ch R = 1 ,2359.316,207.886900,207.886900,207.886900
XS GIS Cut Line= 6
996285.553234854768354.953368038996345.350941963768371.839191071
996418.185217527768401.051575571996442.799843874768408.851075985
996523.889958679768415.422073447996675.634163665768441.508426752
#Sta/Elev= 30
9799.09865.296239819.305 64.89459829.69664.567959840.08764.023939850.478 62.0593
9893.17961.453679903.953  61.1699923.45260.824839936.27659.991169946.85758.18839
9957.34755.593039967.75653.658119977.87852.895949987.94651.105929997.94947.17806
10007.9548.0224110017.9551.3333310028.0155.7397210038.0760.8429910058.28  60.953
10068.4361.7463110078.5861.8026210088.7262.0531610129.3161.6422710139.4661.33378
 10149.6  60.73510159.7560.58058 10169.960.1516210180.0460.2081510200.98 60.5833
#Mann= 3 , 0 , 0
9799.098    0.06       09799.098    0.06       010200.98    0.06       0
#XS Ineff= 2 , 0
       0                               0
Bank Sta=9799.098,10200.98
Exp/Cntr=0.3,0.1

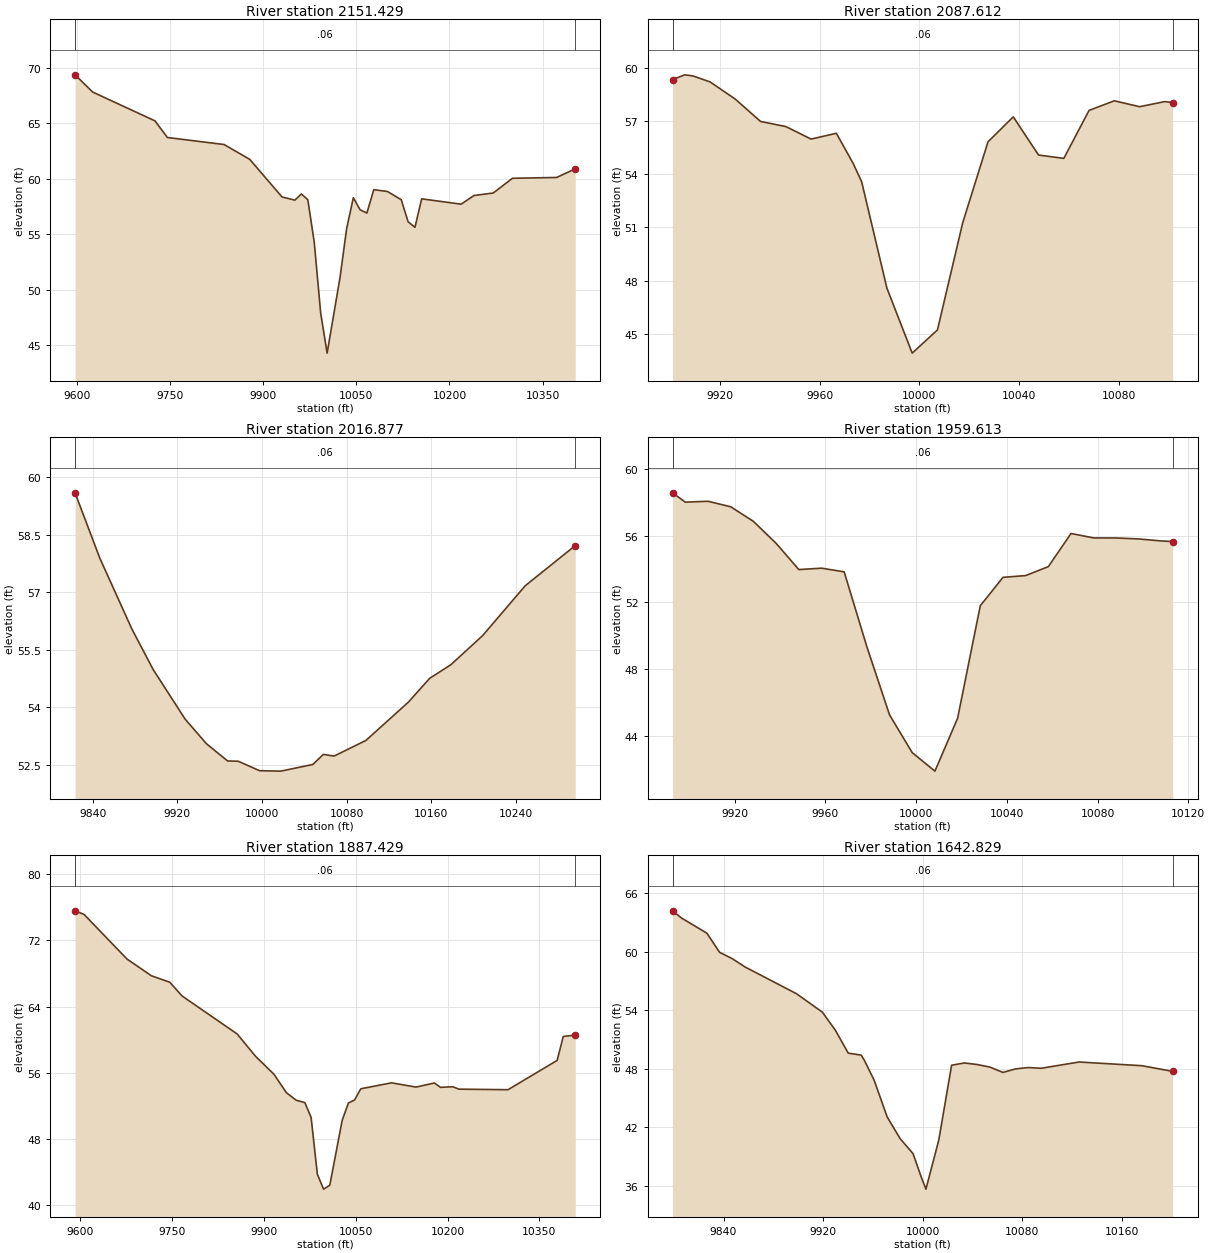
Type RM Length L Ch R = 1 ,2151.429,63.817000,63.817000,63.817000
XS GIS Cut Line= 6
995966.518463966768496.512061136996098.412965865768498.048592102
996214.282505978768516.252289256996389.513612744768564.610515598
996570.363707957768639.349464507996744.442194785768675.265638709
#Sta/Elev= 30
9597.53369.342629626.01967.789859726.09465.204219746.22763.704849837.41363.07389
9878.74561.736039930.611  58.3579951.35758.070859961.73158.627939972.104 58.1161
9982.47754.28882 9992.8547.89908 10003.244.3105910023.9851.1214410034.5855.50471
10045.3658.2880810056.1657.2078810067.21 56.910910078.2659.0127110100.3558.84852
10122.4558.1088310133.4956.1288510144.5455.6267110155.3358.1869310218.8957.70941
10239.6558.4898910270.5558.7132910301.45 60.036410372.5660.1098710402.43 60.8892
#Mann= 3 , 0 , 0
9597.533    0.06       09597.533    0.06       010402.43    0.06       0
#XS Ineff= 2 , 0
       0                               0
Bank Sta=9597.533,10402.43
Exp/Cntr=0.3,0.1

Type RM Length L Ch R = 1 ,2087.612,70.734500,70.734500,70.734500
XS GIS Cut Line= 2
996250.174076319768603.711715475996448.090742975768634.961715475
#Sta/Elev= 24
9901.10459.35445 9905.9959.624579909.36559.559289916.11459.226519926.23858.25283
9936.36256.989979946.48656.70192 9956.6155.992949966.73356.322529973.48354.61122
9976.85753.585849986.98147.571939997.10543.8991110007.2345.2096410017.3551.26681
10027.4855.83984 10037.657.2504610047.7255.0929910057.8554.9034210067.9757.61592
 10078.158.1567210088.2257.8230610098.3458.1132610101.4758.05319
#Mann= 3 , 0 , 0
9901.104    0.06       09901.104    0.06       010101.47    0.06       0
#XS Ineff= 2 , 0
       0                               0
Bank Sta=9901.104,10101.47
Exp/Cntr=0.3,0.1

Type RM Length L Ch R = 1 ,2016.877,57.264400,57.264400,57.264400
XS GIS Cut Line= 3
996161.632409632768667.947826579996404.687965184 768695.72560437
996632.118520766768716.558937684
#Sta/Elev= 20
9823.24759.589479846.767 57.88299876.96256.045159897.09254.989629927.28753.69913
9947.41853.058199967.54852.606479977.61352.599239997.74352.3530110017.8752.34203
10048.0752.5150510058.1352.77861 10068.252.7335410098.3253.1406610138.4954.13881
10158.5754.7572810178.6655.1128410208.78 55.873210248.9557.1685610296.2758.21444
#Mann= 3 , 0 , 0
9823.247    0.06       09823.247    0.06       010296.27    0.06       0
#XS Ineff= 2 , 0
       0                               0
Bank Sta=9823.247,10296.27
Exp/Cntr=0.3,0.1

Type RM Length L Ch R = 1 ,1959.613,72.184100,72.184100,72.184100
XS GIS Cut Line= 2
996229.340742975768746.072826579 996449.82685411768744.336715475
#Sta/Elev= 25
9892.64358.561419898.302  58.0029908.30258.054879918.30357.724079928.30356.84871
9938.30355.532779948.30453.959459958.30454.042689968.30453.822839978.305 49.3332
9988.30545.248799998.30542.9805510008.3141.8719910018.31 45.040710028.3151.78703
 10028.951.8877110038.3153.4931410048.3153.5990510058.3154.1350310068.3156.12203
10078.3155.8571110088.3155.8542410098.3155.7936110108.3155.6731810113.1455.64049
#Mann= 3 , 0 , 0
9892.643    0.06       09892.643    0.06       010113.14    0.06       0
#XS Ineff= 2 , 0
       0                               0
Bank Sta=9892.643,10113.14
Exp/Cntr=0.3,0.1

Type RM Length L Ch R = 1 ,1887.429,244.599400,244.599400,244.599400
XS GIS Cut Line= 6
995940.262784821768828.696213634996220.619000666768833.648981899
996293.475651361768826.340395828996412.845714045768805.485264451
996487.049294398768800.788910866996754.408813861768818.154675152
#Sta/Elev= 30
9591.37375.580949606.11975.14645 9676.1669.766519716.18367.735019746.201 66.9581
9766.21265.300789856.22460.713879886.29758.017289916.44855.841459936.54853.63526
9952.55652.716089966.94452.420529977.108 50.62979987.27243.777279997.43641.97448
10007.5942.4435210027.8750.2840810038.0152.3692210048.1552.7459110058.2954.09273
10108.49 54.810510148.5554.2977710178.5554.7913610188.5654.2651810208.5954.33777
 10218.654.0474710298.8353.9802710379.11 57.521710389.1460.4138510408.6260.56715
#Mann= 3 , 0 , 0
9591.373    0.06       09591.373    0.06       010408.62    0.06       0
#XS Ineff= 2 , 0
       0                               0
Bank Sta=9591.373,10408.62
Exp/Cntr=0.3,0.1

Type RM Length L Ch R = 1 ,1642.829,244.599300,244.599300,244.599300
XS GIS Cut Line= 6
996158.052799255769007.229031206996240.906375193769025.384057199
996341.120833391769054.934027249996422.711078654769075.590919135
996476.879349978769086.067169357996549.594032334769095.399175303
#Sta/Elev= 30
9799.02964.191849806.14163.461619826.61561.901369836.85359.94018 9847.0959.28516
9857.32758.435049898.54255.703999919.39353.814779929.81951.969379940.244 49.6054
 9950.67 49.40599953.20448.865599961.09646.817999971.52143.064889981.94740.84471
9992.33839.30043    999936.8704210002.6735.6705810012.9840.6938310023.2948.36632
 10033.6 48.599710043.9248.4386510054.2348.1714210064.5447.6309610074.8247.99326
10085.0148.13013 10095.248.0558310125.7548.6976710176.1848.3194610200.98 47.7371
#Mann= 3 , 0 , 0
9799.029    0.06       09799.029    0.06       010200.98    0.06       0
#XS Ineff= 2 , 0
       0                               0
Bank Sta=9799.029,10200.98
Exp/Cntr=0.3,0.1

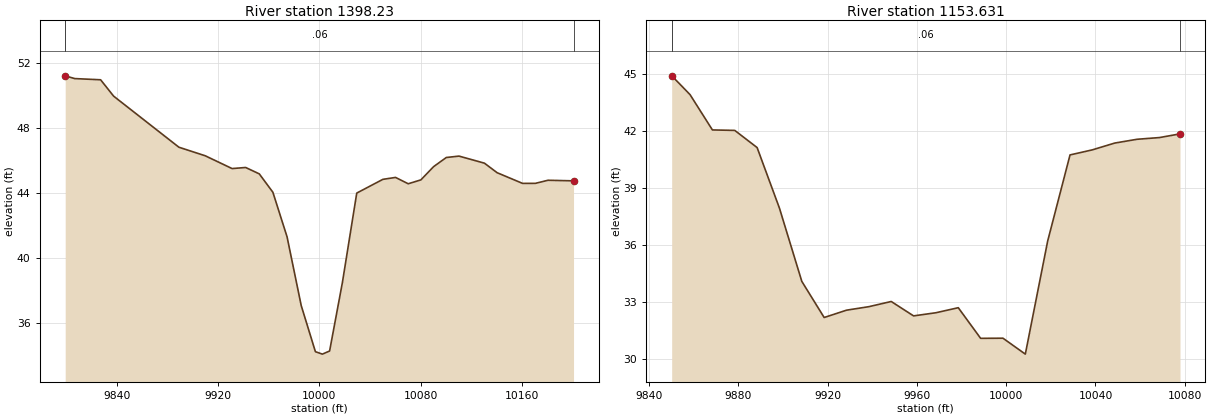
Type RM Length L Ch R = 1 , 1398.23,244.599400,244.599400,244.599400
XS GIS Cut Line= 6
996077.710078588769221.232348591996196.088293025769251.854357922
996284.092025551769291.864243991996310.293271822769299.475281064
996352.427708701769300.067954691996465.047514486769288.247917534
#Sta/Elev= 30
9799.04551.232699806.52551.063099827.04650.989179837.30649.983329888.92946.83821
9909.80846.309669930.96545.524669941.71645.590549952.46845.197879963.22444.06629
9974.424 41.32419985.62937.090029996.83434.2529510002.3834.1034610008.0634.29652
10018.1638.5027210029.5244.0161610050.1644.8605810060.1944.9792310070.2144.58949
10080.22 44.828410090.2445.6407410100.2946.2050110110.3546.2919810130.4645.85709
10140.51 45.269110160.6244.6116410170.6844.6136310180.7344.8048410200.8944.76851
#Mann= 3 , 0 , 0
9799.045    0.06       09799.045    0.06       010200.89    0.06       0
#XS Ineff= 2 , 0
       0                               0
Bank Sta=9799.045,10200.89
Exp/Cntr=0.3,0.1

Type RM Length L Ch R = 1 ,1153.631,154.226400,154.226400,154.226400
XS GIS Cut Line= 2
996206.771298587769464.822826579 996434.20185411769476.975604355
#Sta/Elev= 26
9850.11744.894179853.437 44.50099858.35743.902869868.37242.045969878.38642.02124
  9888.441.117459898.41437.926669908.42934.073849918.44332.172739928.45732.55829
9938.47232.743149948.48633.01577  9958.532.257759968.51432.423539978.52932.68859
9988.54331.076439998.55731.0832810008.5730.2451510018.5936.20082 10028.6 40.7303
10038.6140.9976510040.8541.0781710048.6341.3548810058.6441.5541810068.6641.64421
10077.8741.83846
#Mann= 3 , 0 , 0
9850.117    0.06       09850.117    0.06       010077.87    0.06       0
#XS Ineff= 2 , 0
       0                               0
Bank Sta=9850.117,10077.87
Exp/Cntr=0.3,0.1