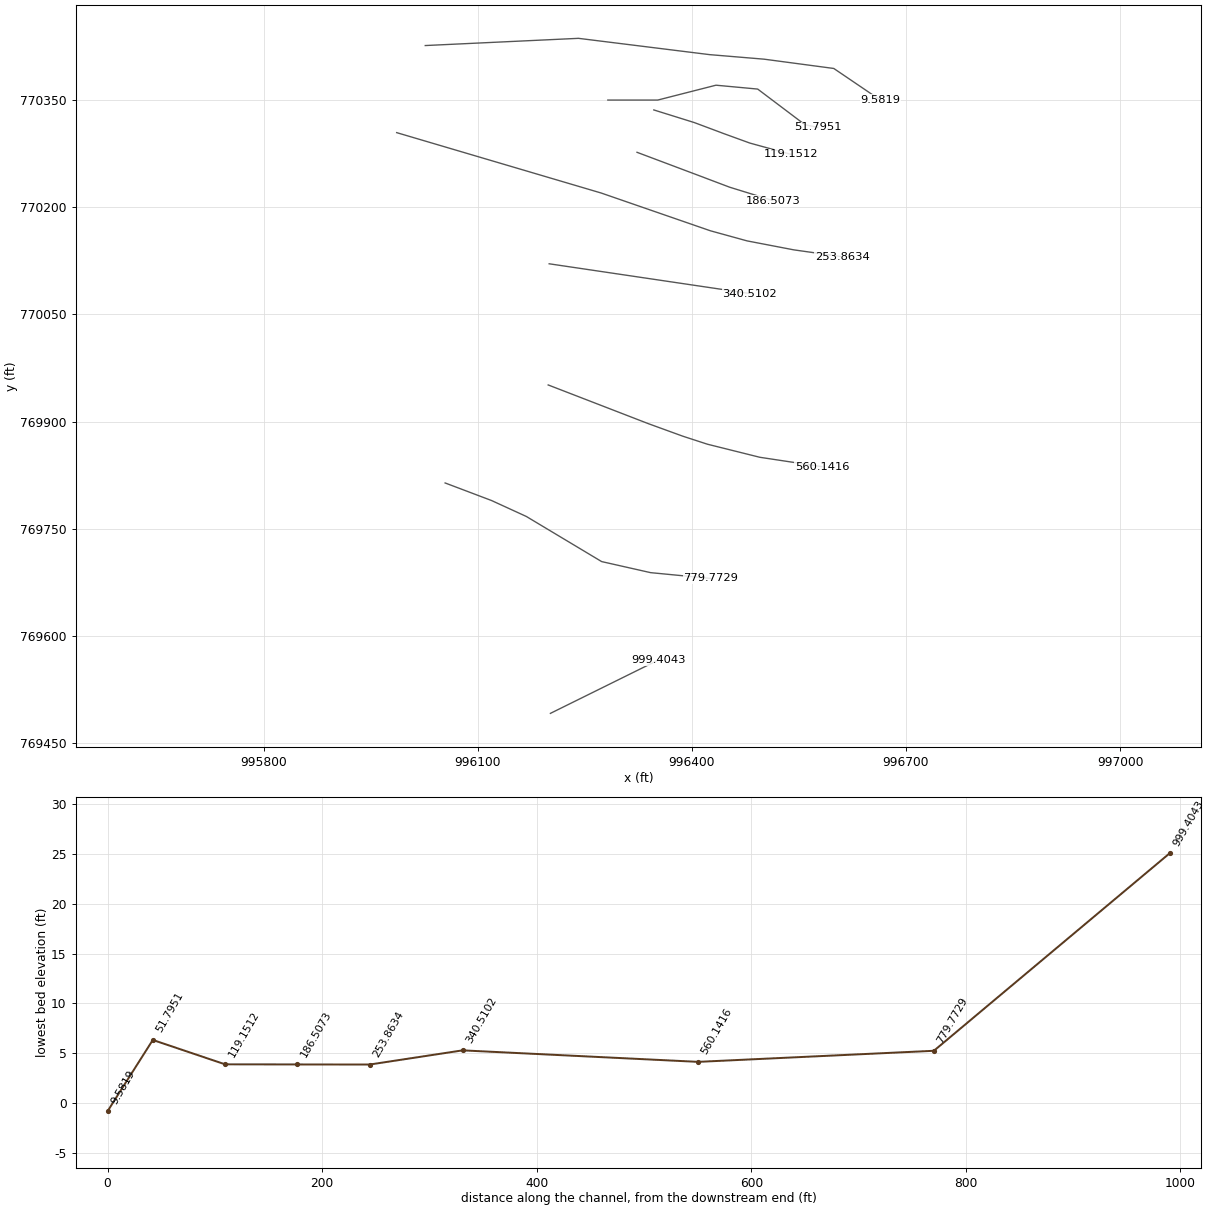
HEC-RAS study 156_ras.prj: 156

--- 156_ras.g01 (geometry) --- (continued)

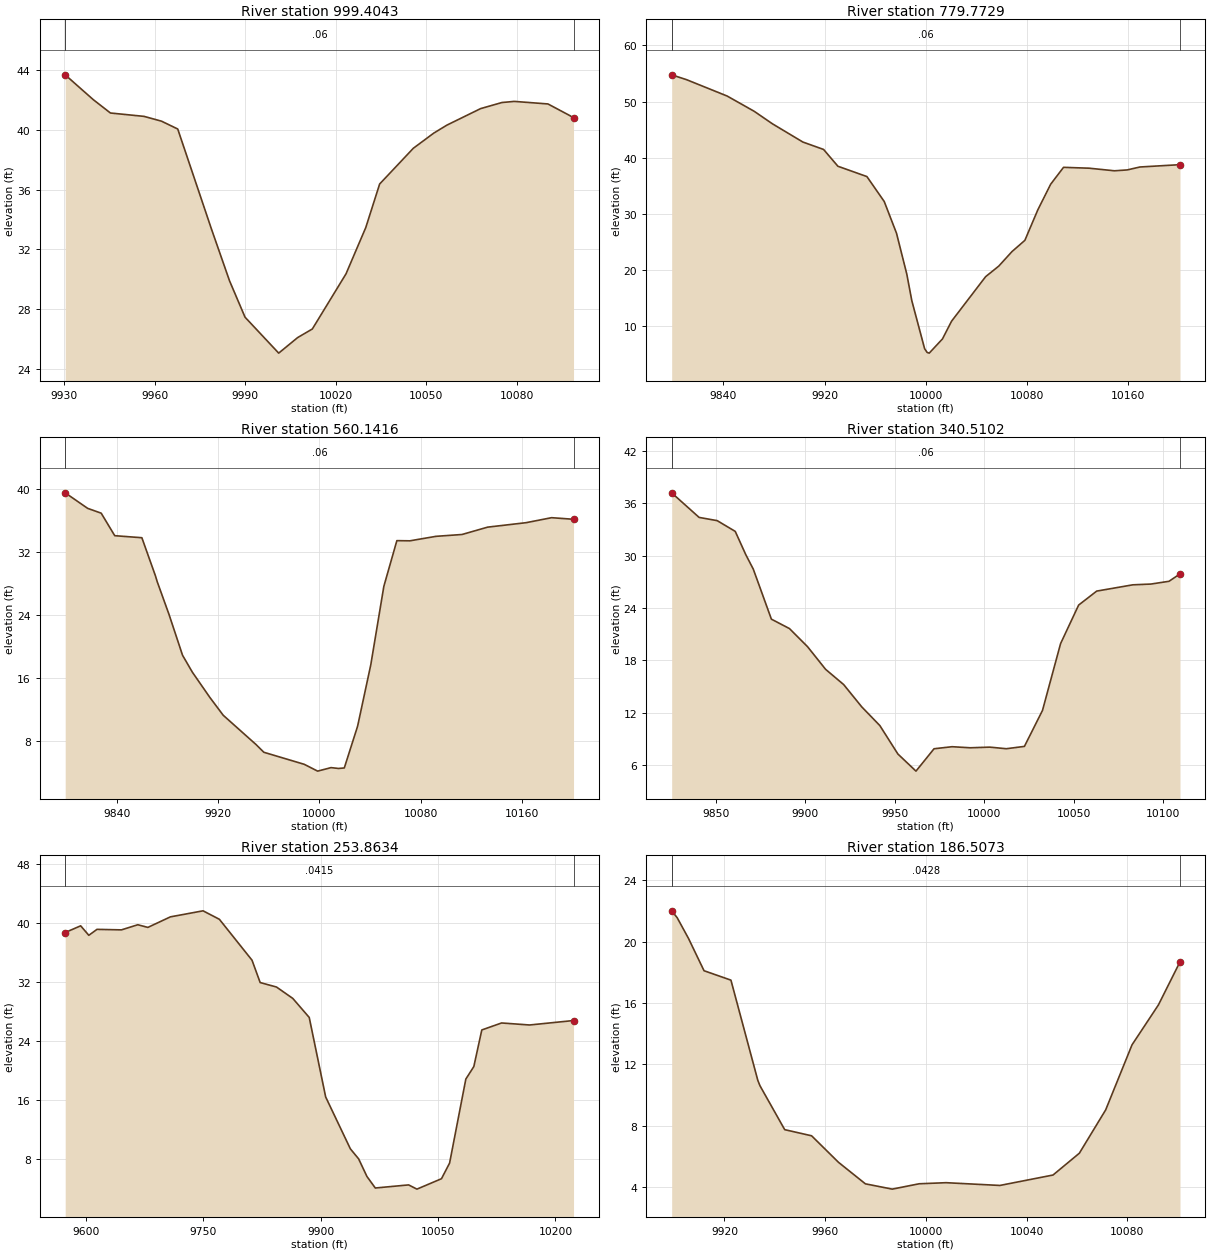
Type RM Length L Ch R = 1 ,999.4043,219.631400,219.631400,219.631400
XS GIS Cut Line= 2
996201.562965184769490.864493251996352.604631841769565.517271012
#Sta/Elev= 25
9930.38743.701959934.22143.01448 9939.7242.034299945.37641.14404 9956.5340.91756
9962.28940.597689967.68540.07206 9978.8433.382379984.85829.897969989.995 27.4622
10001.1525.0554510007.4326.09756 10012.326.6733210023.46 30.3674   1003033.46456
10034.6136.3869410045.77 38.780210052.5639.7989410056.9240.3340710068.0841.43843
10075.1341.8456510079.2341.9215410090.3941.75067 10097.740.9649310098.87 40.8135
#Mann= 3 , 0 , 0
9930.387    0.06       09930.387    0.06       010098.87    0.06       0
#XS Ineff= 2 , 0
       0                               0
Bank Sta=9930.387,10098.87
Exp/Cntr=0.3,0.1

Type RM Length L Ch R = 1 ,779.7729,219.631300,219.631300,219.631300
XS GIS Cut Line= 6
996053.994704063769813.837316871996118.981352301 769789.25696142
996167.750368535769766.922765046996273.401222247769703.628015854
996342.094038475769688.118496736996426.557738837769679.974629381
#Sta/Elev= 30
9799.04554.749369810.81153.886569842.88550.976869864.26848.262859878.74846.02759
9902.76542.788939919.13941.471759930.46938.480759953.38136.647339967.101 32.2037
9976.79326.561859984.89519.320739988.89814.55521    99996.03155910000.995.351794
10002.67 5.2315810013.127.75865110020.3110.9113810047.2118.8276510057.6220.71425
10068.0423.2888810078.2625.2983410088.4930.7138510098.6635.2872210108.8338.28837
10129.0138.1370410149.1137.6731110159.1537.82769 10169.238.34886 10200.938.76431
#Mann= 3 , 0 , 0
9799.045    0.06       09799.045    0.06       0 10200.9    0.06       0
#XS Ineff= 2 , 0
       0                               0
Bank Sta=9799.045,10200.9
Exp/Cntr=0.3,0.1

Type RM Length L Ch R = 1 ,560.1416,219.631400,219.631400,219.631400
XS GIS Cut Line= 6
996198.461322072769951.231810007996339.272376786769896.810644933
996387.239993063 769879.37998669996421.700447342769868.160209935
996495.116671044769849.846246098996582.159021159769836.677399501
#Sta/Elev= 30
9799.00239.516599816.73337.543469827.45436.928799838.17434.065049859.61633.80569
9870.337 28.96629871.76828.208299881.05824.064539891.779 18.85839899.507 16.7144
9913.22113.530429923.941 11.22519949.9647.4918489956.0576.5180289987.9734.988436
9998.6124.11956410009.164.56469210015.154.45883510019.684.52251610030.199.826227
10040.6417.6527310050.9527.6187410061.2533.4340810071.5633.4118810092.1733.98228
10112.7934.2176710133.0235.1521310163.3635.7177610183.5936.3538610200.9436.15245
#Mann= 3 , 0 , 0
9799.002    0.06       09799.002    0.06       010200.94    0.06       0
#XS Ineff= 2 , 0
       0                               0
Bank Sta=9799.002,10200.94
Exp/Cntr=0.3,0.1

Type RM Length L Ch R = 1 ,340.5102,86.646800,86.646800,86.646800
XS GIS Cut Line= 2
 996199.82685411770121.072826579 996481.07685411770079.406159922
#Sta/Elev= 29
9825.19637.206089840.53534.385479850.64434.014999860.75332.782039866.63530.11885
9870.86228.445439880.97122.71168 9891.0821.63075 9901.1919.553489911.29916.95322
9921.40815.203569931.51712.646079941.62610.502799951.7357.2373269961.844  5.2741
9971.9547.8405569982.0638.0749889992.1727.95257910003.118.02691810012.39 7.84474
 10022.58.11133410032.6112.2399710042.72 19.901210052.8324.3272910062.9425.93112
10083.1526.6506510093.26 26.738510103.3727.0553110109.5227.90285
#Mann= 3 , 0 , 0
9825.196    0.06       09825.196    0.06       010109.52    0.06       0
#XS Ineff= 2 , 0
       0                               0
Bank Sta=9825.196,10109.52
Exp/Cntr=0.3,0.1

Type RM Length L Ch R = 1 ,253.8634,67.356100,67.356100,67.356100
XS GIS Cut Line= 6
 995986.06544593770304.928701445996272.756155998770220.264754772
996425.885272473770167.325667709996477.329915345770153.151524484
996542.866923451770140.582605496996610.661924869770131.001488879
#Sta/Elev= 30
9573.51338.684569593.25639.594749603.68338.30623 9614.1139.112479645.39139.04297
9666.24539.739349679.18539.379589707.95340.81024 9749.6641.628859770.51440.48041
9812.22234.925179822.64931.890699843.50331.284859864.35729.735089885.31827.15729
9906.347 16.35779937.8919.3186139948.4497.9581639959.1015.5615279969.7534.002069
10012.334.42265810022.943.84954710054.325.26216310064.697.38748610085.4318.78724
10095.66 20.490410105.8425.4561510131.1326.4060710166.8426.1303810223.0526.73639
#Mann= 3 , 0 , 0
9573.513  0.0415       09573.513  0.0415       010223.05  0.0415       0
#XS Ineff= 2 , 0
       0                               0
Bank Sta=9573.513,10223.05
Exp/Cntr=0.3,0.1

Type RM Length L Ch R = 1 ,186.5073,67.356100,67.356100,67.356100
XS GIS Cut Line= 5
996322.961341454770277.346003035996416.553168655 770242.15812687
996418.413985441770241.425077833996452.878597163770228.408923483
996513.204615975770209.779950435
#Sta/Elev= 21
9899.01222.00392 9901.1921.558979905.67820.211349911.87318.098269922.55717.48512
 9933.2410.949929934.09410.600329943.9247.7369669954.6077.337299 9965.295.608494
9975.9744.2054549986.6573.8599239997.341 4.2086110008.044.27923910029.424.099699
10050.53 4.7791510060.996.20071110071.469.02864710081.9213.2666910092.3915.86527
10100.9818.67538
#Mann= 3 , 0 , 0
9899.012  0.0428       09899.012  0.0428       010100.98  0.0428       0
#XS Ineff= 2 , 0
       0                               0
Bank Sta=9899.012,10100.98
Exp/Cntr=0.3,0.1

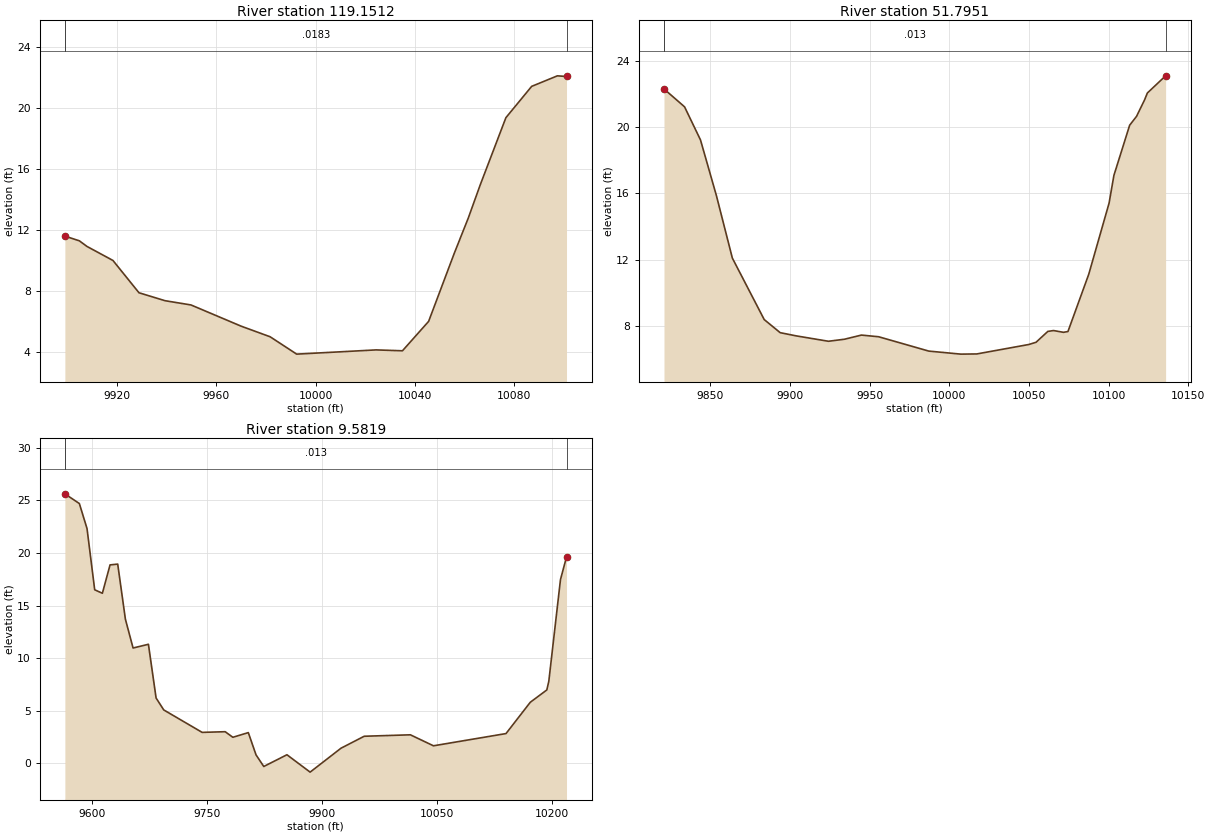
Type RM Length L Ch R = 1 ,119.1512,67.356100,67.356100,67.356100
XS GIS Cut Line= 6
996346.516690764770336.732900368996403.286717769770319.023258549
996441.240830774770304.826807615 996443.10164756770304.093758578
996481.191701191770290.275264612996538.526533025770274.534161785
#Sta/Elev= 20
 9899.0111.602539904.82911.294449907.89610.927249918.37110.006199928.8477.891783
9939.3227.3719519949.7977.0922069969.962 5.70414 9981.665.0080889992.3373.871945
10024.294.14844410034.934.09052510045.476.01759910055.8410.4979310061.4412.78677
10066.2114.9443210076.5819.3592410086.9521.4095110097.3222.1001510100.9822.05624
#Mann= 3 , 0 , 0
 9899.01  0.0183       0 9899.01  0.0183       010100.98  0.0183       0
#XS Ineff= 2 , 0
       09918.877        10087.25       0
Bank Sta=9899.01,10100.98
Exp/Cntr=0.3,0.1

Type RM Length L Ch R = 1 , 51.7951,42.213200,42.213200,42.213200
XS GIS Cut Line= 6
996282.084829241770350.590926915996352.063839883770350.590926915
996433.646992564 770371.41385518 996492.13907212770365.972731486
996558.354389876770316.014134035996576.236098289 770312.38946341
#Sta/Elev= 29
9820.97322.295459833.88821.217449843.88819.223989853.88815.864929863.88812.10413
9883.8888.4003619893.9177.6110969904.0177.4176149924.2167.0937979934.3167.217391
9944.8767.466209 9955.667.3662159987.1736.50168910007.266.319067 10017.36.330006
10049.916.89804510054.487.03267810061.887.68646210065.457.73957910071.737.632696
10074.517.68017510087.5411.1232410100.3315.4175710103.3617.0872110113.2420.10906
10117.5720.6447510122.6721.6487210124.3522.0491410135.8123.08485
#Mann= 3 , 0 , 0
9820.973   0.013       09820.973   0.013       010135.81   0.013       0
#XS Ineff= 2 , 0
       09917.807        10059.82       0
Bank Sta=9820.973,10135.81
Exp/Cntr=0.3,0.1

Type RM Length L Ch R = 1 ,  9.5819,0.000000,0.000000,0.000000
XS GIS Cut Line= 6
996026.135023713770426.993853927996240.870577842770437.103192657
996424.703626364770414.260032773996501.106553406770407.893122166
996598.789756328770394.868695125996664.099464327770350.590926915
#Sta/Elev= 30
9564.49725.626079583.38324.702779593.39422.321969603.40516.501519613.41616.16951
9623.42718.867229633.43818.941839643.44913.704539653.46110.963079673.48311.31837
9683.4946.2075919693.5055.074081 9743.562.9403259773.5933.0042459783.6322.474352
9803.7862.9189369813.8620.8010459823.939-0.30332 9854.170.8122219884.401-0.83925
9924.7081.4359239954.9392.57167610015.192.70912810045.311.66454710139.932.827489
 10171.65.80419510193.166.97551810195.767.80287210210.9817.4728710218.8419.61667
#Mann= 3 , 0 , 0
9564.497   0.013       09564.497   0.013       010218.84   0.013       0
#XS Ineff= 2 , 0
       09952.918        10044.59       0
Bank Sta=9564.497,10218.84
Exp/Cntr=0.3,0.1